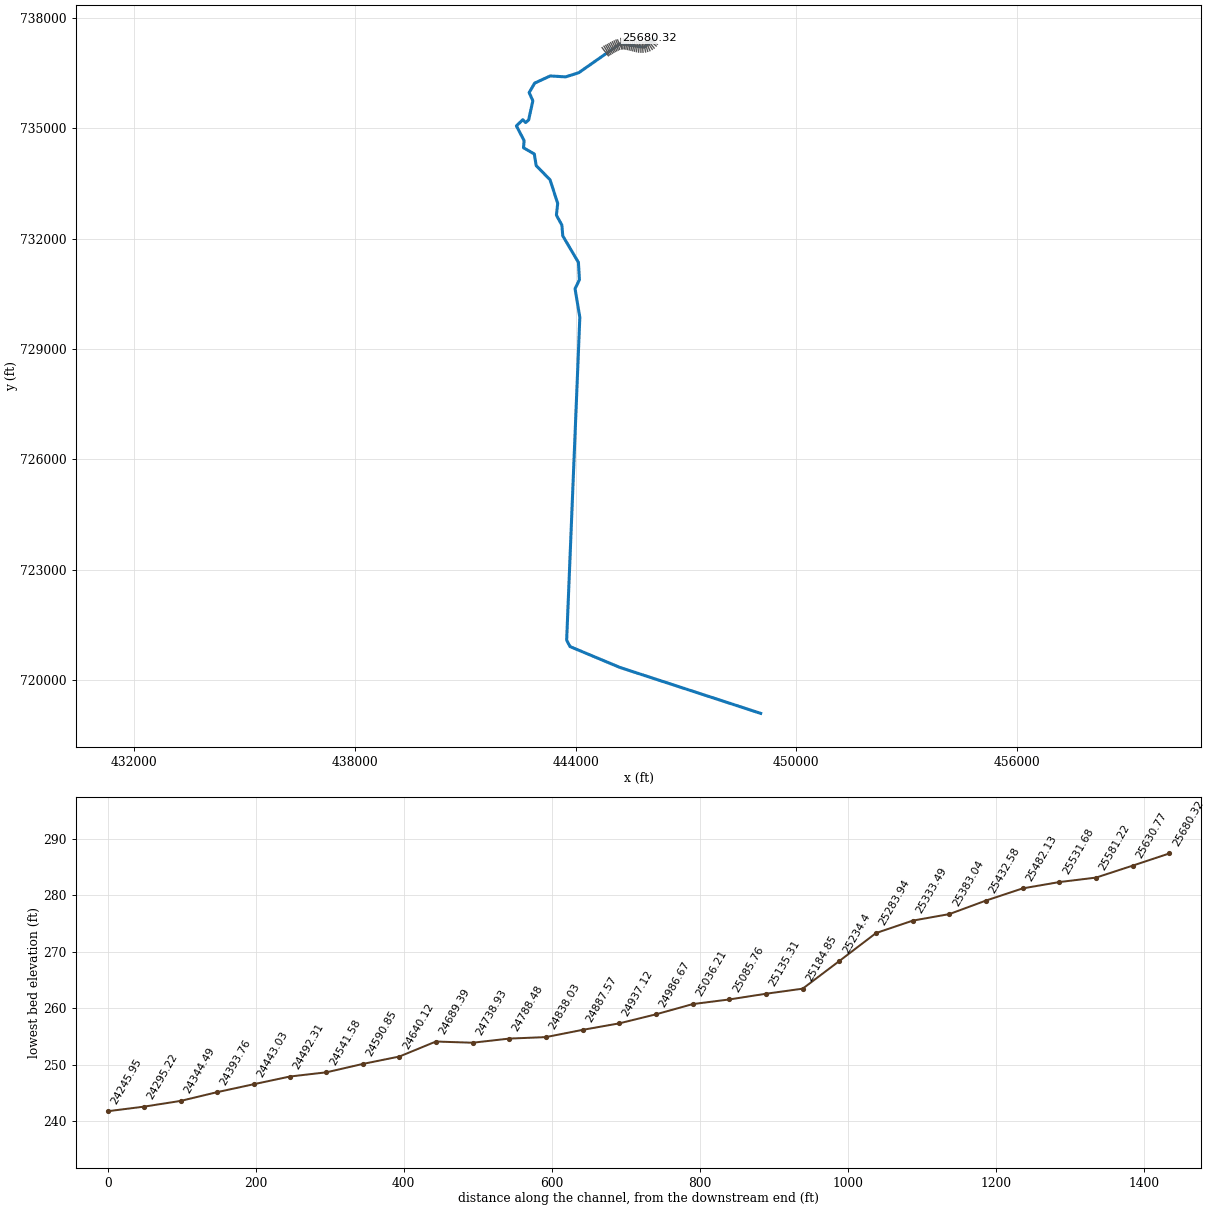
--- 708_ras.prj (project) ---

Proj Title=708
Current Plan=p01
Default Exp/Contr=0.3,0.1
English Units
Geom File=g01
Flow File=f01
Plan File=p01
Y Axis Title=Elevation
X Axis Title(PF)=Main Channel Distance
X Axis Title(XS)=Station
BEGIN DESCRIPTION:
RFD model 708 exported to HEC-RAS
END DESCRIPTION:

--- 708_ras.p01 (plan) ---

Plan Title=Plan 01
Program Version=4.10
Short Identifier=Plan 01
Geom File=g01
Flow File=f01
Subcritical Flow
Calc Critical at every XS
Secant Critical Depth

--- 708_ras.f01 (steady flow) ---

Flow Title=Flow 01
Program Version=5.01
Number of Profiles= 6
Profile Names=10yr,25yr,50yr,100yr,100plus,500yr
River Rch & RM=708,129,25680.32
   94.88  173.57  255.59   342.7  500.34 1084.21
River Rch & RM=708,129,24344.49
   98.03  179.37  264.19  354.27  517.23 1115.86
River Rch & RM=708,129,24091.27
  110.15  201.74  297.35  398.93  582.44 1236.78
River Rch & RM=708,129,23892.58
  120.95  221.62  326.79  438.52  640.24 1341.99
River Rch & RM=708,129,23744.77
  124.36  227.95  336.18  451.19  658.74 1375.59
River Rch & RM=708,129, 23695.5
  126.16  231.28  341.15  457.89  668.52 1393.39
River Rch & RM=708,129,23547.69
  128.63  235.86  347.96  467.09  681.95  1417.7
River Rch & RM=708,129,23399.88
  130.87  240.01  354.13  475.41   694.1 1439.67
River Rch & RM=708,129,23252.06
  133.32  244.56  360.89  484.54  707.43 1463.68
River Rch & RM=708,129,23104.25
  134.21  246.21  363.34  487.85  712.26 1472.37
River Rch & RM=708,129,23054.98
  135.77  249.08  367.62  493.63   720.7 1487.54
River Rch & RM=708,129,22907.17
  137.32  251.96  371.89   499.4  729.12 1502.64
River Rch & RM=708,129,22759.36
   138.2   253.6  374.33  502.69  733.92 1511.25
River Rch & RM=708,129,22710.09
  139.52  256.05  377.98  507.61  741.12 1524.12
River Rch & RM=708,129,22562.28
     190  349.06  515.77  692.95  1011.7 1992.15
River Rch & RM=708,129,22463.74
  191.44  351.73  519.76  698.34 1019.57 2005.63
River Rch & RM=708,129,22315.92
  194.73  357.84  528.85  710.62 1037.51  2036.3
River Rch & RM=708,129,22217.38
  196.16   360.5  532.82  715.98 1045.34 2049.66
River Rch & RM=708,129,21921.76
  225.22  414.38  612.99   824.2 1203.32 2315.65
River Rch & RM=708,129,21823.22
  226.42   416.6   616.3  828.66 1209.85 2326.54
River Rch & RM=708,129,21626.14
  228.21  419.93  621.25  835.35 1219.61 2342.84
River Rch & RM=708,129, 21527.6
  239.99  441.86  653.96  879.58 1284.19 2450.41
River Rch & RM=708,129,21429.06
  241.55  444.75  658.28  885.43 1292.73 2464.61
River Rch & RM=708,129,21330.52
  242.48  446.51  660.92  889.03 1297.98 2473.47
River Rch & RM=708,129,21133.43
  245.11  451.45  668.34  899.12 1312.71 2498.21
River Rch & RM=708,129,20912.99
  246.41   453.9  672.02  904.14 1320.04 2510.54
River Rch & RM=708,129,20472.11
  283.28  522.93  775.39 1044.43 1524.87 2848.62
River Rch & RM=708,129,20251.67
   285.8  527.68  782.54 1054.17 1539.08 2872.03
River Rch & RM=708,129,20161.11
  287.42  530.73  787.13 1060.42 1548.21 2887.04
River Rch & RM=708,129,19860.49
   288.5  532.77  790.19 1064.58 1554.29 2897.04
River Rch & RM=708,129, 19645.9
  290.12  535.81  794.77 1070.82  1563.4    2912
River Rch & RM=708,129,19431.31
  319.02  590.29  876.71 1182.47 1726.41    3178
River Rch & RM=708,129,19216.73
  322.88  597.57  887.66 1197.38 1748.18 3213.23
River Rch & RM=708,129,19002.14
  324.24  600.15  891.57 1202.73 1755.98    3226
River Rch & RM=708,129,18787.55
  326.45  604.35  897.92 1211.42 1768.67 3246.71
River Rch & RM=708,129,18572.97
  403.59  749.37 1115.72 1507.67  2201.2  3930.8
River Rch & RM=708,129,18506.03
   404.4  750.91 1118.05 1510.87 2205.86 3938.18
River Rch & RM=708,129,18266.32
  410.71   762.9  1136.2 1535.71 2242.14 3995.54
River Rch & RM=708,129,18026.61
  412.49  766.27 1141.31 1542.71 2252.35 4011.66
River Rch & RM=708,129, 17786.9
  413.94  769.03 1145.49 1548.42  2260.7 4024.83
River Rch & RM=708,129,17547.18
   430.6  800.74 1193.48 1614.15 2356.65 4175.82
River Rch & RM=708,129,17307.47
  432.47  804.32 1198.92 1621.62 2367.57  4193.1
River Rch & RM=708,129,17073.26
  456.38  850.07 1268.42 1717.11 2506.98  4412.5
River Rch & RM=708,129,16828.04
  457.61  852.42 1271.99 1722.02 2514.16 4423.78
River Rch & RM=708,129,16588.33
  460.66  858.28 1280.91  1734.3 2532.07 4451.93
River Rch & RM=708,129,16348.62
     588 1098.82 1643.49 2228.81 3254.06  5540.6
River Rch & RM=708,129,16021.54
  590.17 1102.99 1649.84 2237.55 3266.82 5559.93
River Rch & RM=708,129,15378.59
 1121.24 2101.08 3149.97 4276.69 6243.97 9713.96
River Rch & RM=708,129,15284.07
 1123.64 2105.77 3157.19 4286.72 6258.61 9734.65
River Rch & RM=708,129,15112.96
 1124.36 2107.17 3159.35 4289.73    6263 9740.85
River Rch & RM=708,129,14906.71
 1125.08 2108.57 3161.52 4292.73 6267.39 9747.05
River Rch & RM=708,129, 14670.5
 1152.64 2162.66 3245.05 4409.03 6437.18 9987.68
River Rch & RM=708,129,14430.92
 1154.31 2165.92 3250.07    4416 6447.36   10002
River Rch & RM=708,129,14335.77
  1154.9 2167.07 3251.85 4418.48 6450.9810007.12
River Rch & RM=708,129,14092.39
 1161.43 2179.97 3271.86 4446.44 6491.8110065.34
River Rch & RM=708,129,13849.02
 1162.43 2181.96 3274.97 4450.81 6498.1810074.52
River Rch & RM=708,129,13605.64
 1333.51 2513.12 3782.34 5152.12  7522.111480.27
River Rch & RM=708,129,13362.27
  1334.7 2515.49 3786.03  5157.3 7529.6611490.92
River Rch & RM=708,129,13118.89
 1336.22 2518.51 3790.73  5163.9 7539.2911504.48
River Rch & RM=708,129,12875.52
 1339.45 2524.95 3800.77    5178 7559.8811533.51
River Rch & RM=708,129,12632.14
 1340.39 2526.84 3803.74 5182.18 7565.9911542.21
River Rch & RM=708,129,12388.77
 1386.48 2618.76 3947.17 5383.63  7860.111956.05
River Rch & RM=708,129,12145.39
 1481.77 2808.22 4242.36  5797.7 8464.6412797.13
River Rch & RM=708,129, 11627.6
 1485.05 2814.81 4252.68 5812.24 8485.8812826.83
River Rch & RM=708,129,10607.93
 1542.17 2929.84  4433.3 6067.34 8858.3113348.67
River Rch & RM=708,129,9634.553
 1553.97 2953.66 4470.78 6120.36 8935.7313457.17
River Rch & RM=708,129,8417.836
 1635.31 3119.93 4734.24 6495.33 9483.18 14231.4
River Rch & RM=708,129,7444.463
 1646.99 3144.31 4773.33 6551.54 9565.2514349.65
River Rch & RM=708,129, 6471.09
 1654.97 3161.08 4800.34 6590.51 9622.1414432.11
River Rch & RM=708,129,4767.687
  1714.7 3288.13 5006.32 6889.3910058.5115070.49
Boundary for River Rch & Prof#=708,129,1
Up Type= 0
Dn Type= 2
Boundary for River Rch & Prof#=708,129,2
Up Type= 0
Dn Type= 2
Boundary for River Rch & Prof#=708,129,2
Up Type= 0
Dn Type= 2
Boundary for River Rch & Prof#=708,129,2
Up Type= 0
Dn Type= 2
Boundary for River Rch & Prof#=708,129,2
Up Type= 0
Dn Type= 2
Boundary for River Rch & Prof#=708,129,2
Up Type= 0
Dn Type= 2

--- 708_ras.g01 (geometry) ---

Geom Title=708
Program Version=4.10

River Reach=708,129
Reach XY= 30
 446136.99508509737410.766051948445858.241054446 737205.63830848
445210.551373094737300.689090967444086.019488692 736513.66085197
443728.814168245 736399.76930052443311.211812913736425.653744042
 442886.70693934736230.657602891442736.861697197735972.726985767
442837.272866458735748.912525699 442722.77213043735229.792453781
442639.941911221 735157.31601198442564.014210224  735234.9693425
442389.725623906735067.583274439442600.252431154734665.511585265
442582.996135771734472.241073683442876.353161931734303.129376084
442928.122049004733987.339165241443304.574662179733601.767825752
443512.894639492732959.403725237443478.044552267732639.134541422
443627.065122366 732367.75547865 443649.97069329732078.301827297
 444076.65977186731354.507562801444103.634239018730882.779887587
443984.677020758730639.109420732444114.516548306729862.443247721
443756.285912216721083.133911699443847.354281008720908.558494255
445208.417741358720339.225027308449032.624270141719091.609309271

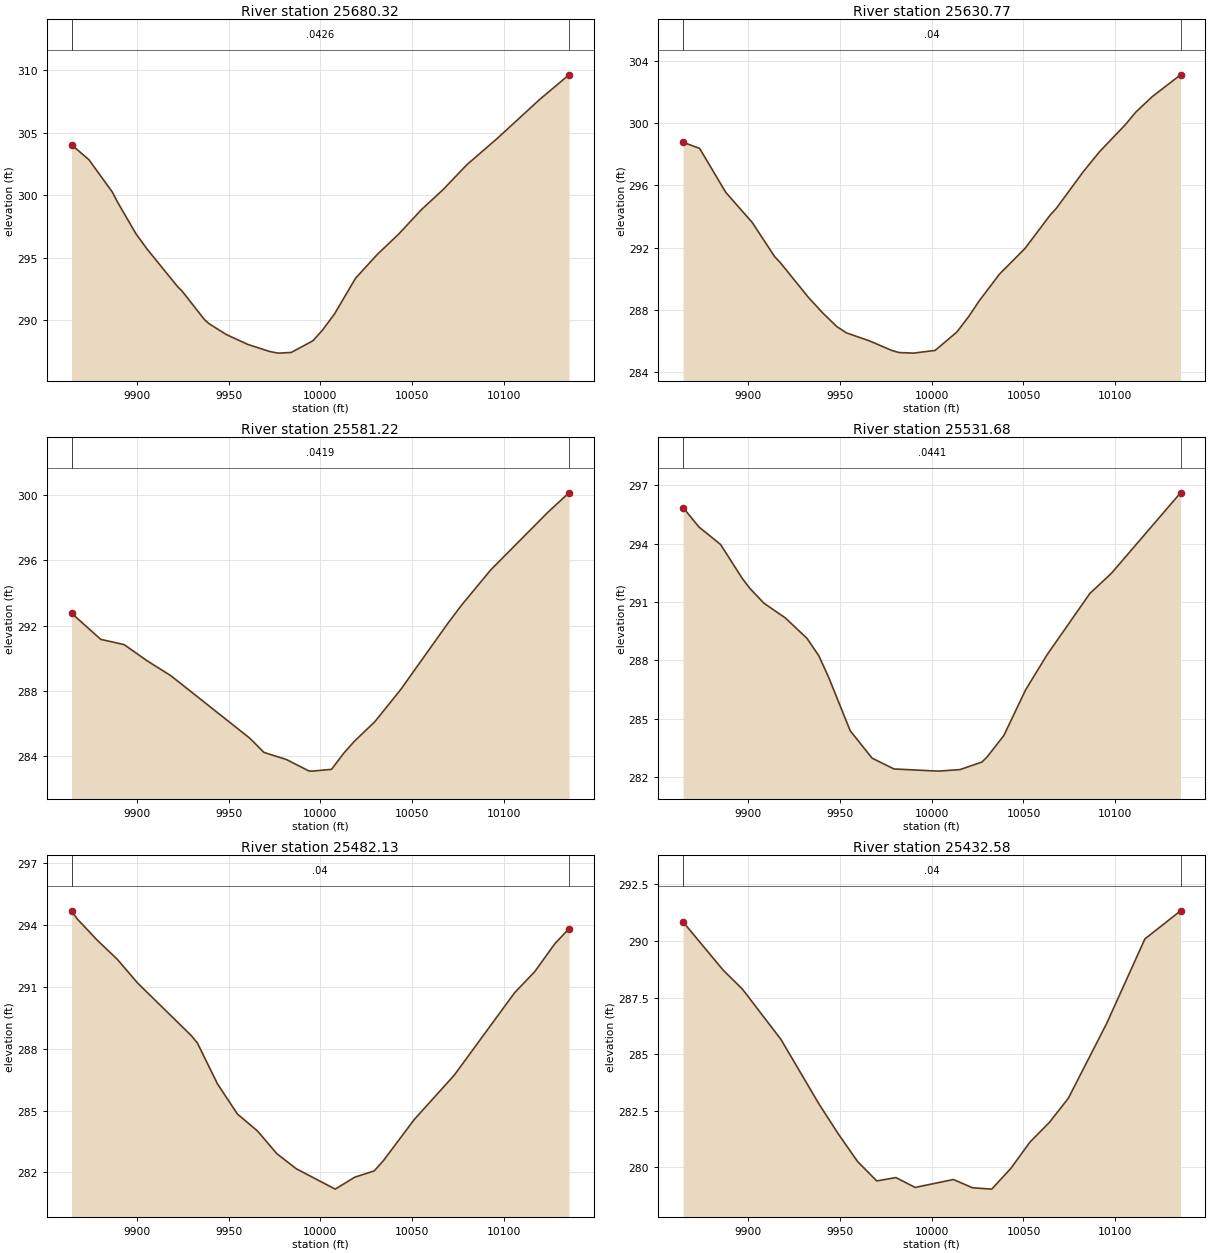
Type RM Length L Ch R = 1 ,25680.32,49.546500,49.546500,49.546500
XS GIS Cut Line= 6
446222.127348873737288.946842857446162.398751675737335.446068589
446081.933352473737384.857648209446055.656757563737402.712826516
446031.892461715737421.486390028446003.205432507737448.077888816
#Sta/Elev= 27
9864.337304.03599873.875302.8268  9886.5 300.2719889.632299.39679899.439296.9242
9905.418295.71739922.346 292.665 9924.46292.36569936.842290.05859939.306289.7328
9948.779288.85989960.561288.06829972.343287.50929977.043287.37679984.124287.4293
9995.906288.3556   10001289.178310007.59290.468810019.25293.364410030.91 295.236
10042.87296.908810054.96 298.816 10067.1 300.46410079.84302.420210096.55304.5418
10119.58307.641710135.66309.6212
#Mann= 3 , 0 , 0
9864.337  0.0426       09864.337  0.0426       010135.66  0.0426       0
#XS Ineff= 2 , 0
       0                               0
Bank Sta=9864.337,10135.66
Exp/Cntr=0.3,0.1

Type RM Length L Ch R = 1 ,25630.77,49.546400,49.546400,49.546400
XS GIS Cut Line= 6
446191.526622739737238.973139332446127.059813152737296.781666413
446068.029575743737335.839763554446045.600359049737352.983842508
446011.249187227737384.335811007445984.482199262737412.865096765
#Sta/Elev= 28
9864.336298.76319873.338298.37649887.605295.55159902.124293.60259914.345291.4086
 9917.26291.04889932.732288.79499940.555287.79559948.204286.92269953.507 286.516
9965.868286.01099978.229285.38839982.179285.25519990.067285.217810001.79285.3932
10013.57286.561410020.21287.5811 10025.6288.536910036.88290.290110050.83291.9456
10064.37294.061910067.85294.512210082.68296.887310091.45298.156510105.66299.9091
10111.15300.693510120.28301.702810135.65 303.099
#Mann= 3 , 0 , 0
9864.336    0.04       09864.336    0.04       010135.65    0.04       0
#XS Ineff= 2 , 0
       0                               0
Bank Sta=9864.336,10135.65
Exp/Cntr=0.3,0.1

Type RM Length L Ch R = 1 ,25581.22,49.546500,49.546500,49.546500
XS GIS Cut Line= 6
446135.206350296737182.479604564446072.272063629737262.321079584
446053.056604314737289.171266763446051.933601477737290.826218312
446035.759846487737313.282127971445967.905565402737396.005554902
#Sta/Elev= 20
9864.319 292.7569880.262291.15579892.995 290.8369905.728 289.8329918.461288.9362
9961.576 285.1079969.277284.23979981.574283.80279993.871283.10179995.661283.0949
10006.14283.204310012.86284.199210018.47284.907510029.87 286.13310043.83288.0821
 10069.7292.155310077.18293.267510092.94295.401310124.48298.969210135.67 300.121
#Mann= 3 , 0 , 0
9864.319  0.0419       09864.319  0.0419       010135.67  0.0419       0
#XS Ineff= 2 , 0
       0                               0
Bank Sta=9864.319,10135.67
Exp/Cntr=0.3,0.1

Type RM Length L Ch R = 1 ,25531.68,49.546400,49.546400,49.546400
XS GIS Cut Line= 6
446084.204695342737147.630890137 446033.98916119737228.173032125
446012.058118922737261.350865937446010.935116085737263.005817486
445986.464390667 737300.26489138445939.706104413 737377.28822351
#Sta/Elev= 23
9864.315295.85519872.999294.85399884.783293.95579896.568292.21819900.614291.7153
9908.352290.94249920.137290.17759931.921289.13079938.417 288.2299943.705287.1325
 9955.49284.38149967.413282.9722  9979.4282.415410003.39282.304510015.35 282.382
10027.31282.770410030.03283.019510039.28284.133810051.12286.473710062.81 288.277
10086.21291.438210097.91292.467910135.68296.6114
#Mann= 3 , 0 , 0
9864.315  0.0441       09864.315  0.0441       010135.68  0.0441       0
#XS Ineff= 2 , 0
       0                               0
Bank Sta=9864.315,10135.68
Exp/Cntr=0.3,0.1

Type RM Length L Ch R = 1 ,25482.13,49.546500,49.546500,49.546500
XS GIS Cut Line= 6
446021.118331541737112.087309038445980.530985427737205.082878575
445969.389890447737236.355103066445968.840448192737238.278150962
445957.344476453737269.711741862445915.949577602737362.047916394
#Sta/Elev= 22
9864.336294.69249867.514294.29259878.425 293.2619889.336 292.3369900.246291.2013
 9929.63288.63849932.979288.2791 9943.89286.30129954.801284.83079965.802284.0057
 9976.33282.90399986.946282.173610008.16281.186510018.81281.766210029.45282.0724
10034.47282.574110051.22284.561410073.14286.724610106.02290.721110116.98291.7417
10127.94293.098210135.66293.8263
#Mann= 3 , 0 , 0
9864.336    0.04       09864.336    0.04       010135.66    0.04       0
#XS Ineff= 2 , 0
       0                               0
Bank Sta=9864.336,10135.66
Exp/Cntr=0.3,0.1

Type RM Length L Ch R = 1 ,25432.58,49.546400,49.546400,49.546400
XS GIS Cut Line= 4
445961.385077537737094.031237254445921.749794202737222.743646997
445921.200351946737224.666694892445882.315190595737353.609390628
#Sta/Elev= 20
9864.323290.84369886.264288.70689896.727287.87149917.654285.65819938.581282.7821
9949.044281.47039959.507280.25539969.971279.39659980.434 279.5459990.898279.1091
10011.79279.458410022.24 279.09410032.68279.034110043.13279.951710053.57 281.117
10064.02281.972610074.46283.047710095.35286.349810116.24 290.09210135.68291.3338
#Mann= 3 , 0 , 0
9864.323    0.04       09864.323    0.04       010135.68    0.04       0
#XS Ineff= 2 , 0
       0                               0
Bank Sta=9864.323,10135.68
Exp/Cntr=0.3,0.1

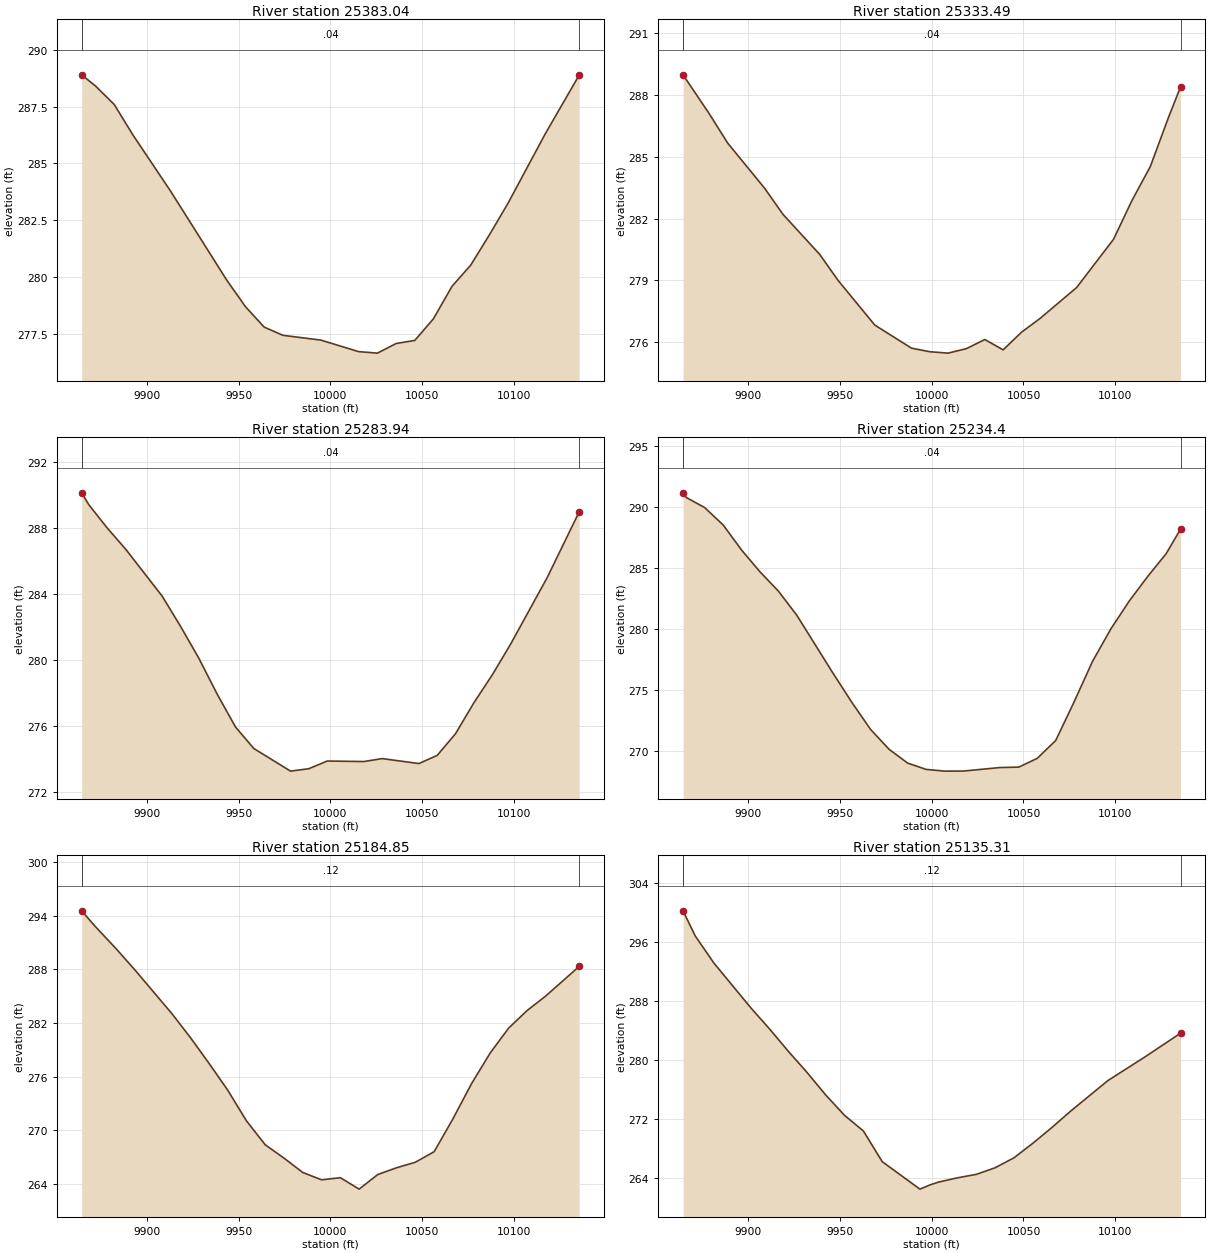
Type RM Length L Ch R = 1 ,25383.04,49.546500,49.546500,49.546500
XS GIS Cut Line= 6
445903.232446509737077.654810842445880.352180332737184.815169385
445874.109697956737209.132190928  445873.5602557737211.055238823
445867.498044589 737235.47099888445847.481282973737343.145834235
#Sta/Elev= 21
9864.319288.90949871.829288.41949882.055287.6042 9892.28286.25849912.731283.7907
9943.407279.86199953.633278.68729963.858277.78419974.085277.42089994.734277.2106
10015.37276.701410025.67276.634910035.85277.059610046.02277.194410056.19278.1477
10066.36279.583310076.53280.514510086.71281.847510096.88283.244610117.22286.3104
10135.68288.8944
#Mann= 3 , 0 , 0
9864.319    0.04       09864.319    0.04       010135.68    0.04       0
#XS Ineff= 2 , 0
       0                               0
Bank Sta=9864.319,10135.68
Exp/Cntr=0.3,0.1

Type RM Length L Ch R = 1 ,25333.49,49.546400,49.546400,49.546400
XS GIS Cut Line= 6
445832.999028419737070.735696744445826.197760368737147.295976208
445824.902160545737205.082738181445824.928824841737207.082560427
445824.300139944737256.106310273445817.100282982737341.436383924
#Sta/Elev= 22
9864.337288.96939878.657287.07639888.697285.65759908.776283.47429918.815282.2064
9938.894280.25789948.905278.9992 9968.91 276.8349988.915275.71699998.917275.5421
10008.92275.474910018.92275.694410028.92276.134910038.92275.632710048.92276.4889
10058.95277.150610079.02278.6585 10099.1280.992310109.13282.868110119.17284.5207
 10129.2  286.9310135.66288.3819
#Mann= 3 , 0 , 0
9864.337    0.04       09864.337    0.04       010135.66    0.04       0
#XS Ineff= 2 , 0
       0                               0
Bank Sta=9864.337,10135.66
Exp/Cntr=0.3,0.1

Type RM Length L Ch R = 1 ,25283.94,49.546500,49.546500,49.546500
XS GIS Cut Line= 5
445775.273383494737071.071323603445774.464296802737135.844782958
445775.360116115737205.743298774445775.386780411 737207.74312102
445777.185446848737342.403006817
#Sta/Elev= 23
9864.317290.10899868.246289.38649878.247287.98429888.248286.71069908.249283.8576
 9918.25282.03349928.251280.10069938.252277.93099948.253 275.9429958.253274.6425
9978.255273.27659988.256273.42349998.257273.887610018.26273.855910028.26274.0345
10048.26273.734310058.26274.229710068.26275.542910078.26277.409610088.26279.0921
10098.27280.951110118.27284.986710135.67288.9519
#Mann= 3 , 0 , 0
9864.317    0.04       09864.317    0.04       010135.67    0.04       0
#XS Ineff= 2 , 0
       0                               0
Bank Sta=9864.317,10135.67
Exp/Cntr=0.3,0.1

Type RM Length L Ch R = 1 , 25234.4,49.546400,49.546400,49.546400
XS GIS Cut Line= 6
445712.044709936737073.193345555445717.703496765737148.799166112
445725.679907709 737207.09289104445726.149188776737209.037055457
445734.414066226737267.779016756445740.838521471 737342.84128187
#Sta/Elev= 27
9864.346291.13979866.158290.75419876.185289.92479886.213 288.5079896.241286.4537
9906.269284.66999916.297283.09189926.325281.11649946.422276.28529956.515273.9392
9966.608271.74569976.701270.11749986.794268.98769996.888268.468410007.02268.3274
10017.12268.331110037.32268.623210047.42268.654610057.51 269.37410067.57270.8365
 10077.6273.997610087.64277.320110097.68279.990910107.71282.273210117.75 284.285
10127.79 286.14610135.66288.1597
#Mann= 3 , 0 , 0
9864.346    0.04       09864.346    0.04       010135.66    0.04       0
#XS Ineff= 2 , 0
       0                               0
Bank Sta=9864.346,10135.66
Exp/Cntr=0.3,0.1

Type RM Length L Ch R = 1 ,25184.85,49.546400,49.546400,49.546400
XS GIS Cut Line= 6
445653.949926278737086.218900156445665.882645529737166.191894257
 445677.51668714737218.718496016445677.985968207737220.662660433
445693.177288499737290.818723382445701.827616913737353.097549145
#Sta/Elev= 26
9864.342294.52639871.458292.84719883.331290.24669893.442287.90819913.663283.0112
9923.774 280.3299933.885277.46039943.995274.48889954.222271.05629964.464268.3828
9974.707266.89359984.949265.28849995.191264.469310005.44264.705510015.67263.4288
 10025.9265.068110036.13265.817310046.36266.4333 10056.6267.613510066.83271.2819
   10077275.2187 10087.1278.6252 10097.2281.418410107.29 283.38610117.39284.9996
10135.66288.3082
#Mann= 3 , 0 , 0
9864.342    0.12       09864.342    0.12       010135.66    0.12       0
#XS Ineff= 2 , 0
       0                               0
Bank Sta=9864.342,10135.66
Exp/Cntr=0.3,0.1

Type RM Length L Ch R = 1 ,25135.31,49.546500,49.546500,49.546500
XS GIS Cut Line= 6
445602.296573215737098.467274534445615.737057935 737172.59497117
445629.353466571737230.344100991445629.822747638737232.288265408
445647.692385458737309.207885142445657.086169772 737364.11333189
#Sta/Elev= 24
9864.331 300.244 9870.97296.83789881.133293.17459901.459287.04869911.622284.2073
9921.785281.19799931.949278.34289942.138275.28739952.412 272.5289962.687270.4122
9972.961266.25339993.509262.5324    9999263.102310003.78263.494610014.05264.0673
10024.32264.535610034.58265.430410044.85266.782210055.12268.748810065.38270.8562
10075.65273.083810095.99277.231610116.28280.451910135.67283.6594
#Mann= 3 , 0 , 0
9864.331    0.12       09864.331    0.12       010135.67    0.12       0
#XS Ineff= 2 , 0
       0                               0
Bank Sta=9864.331,10135.67
Exp/Cntr=0.3,0.1

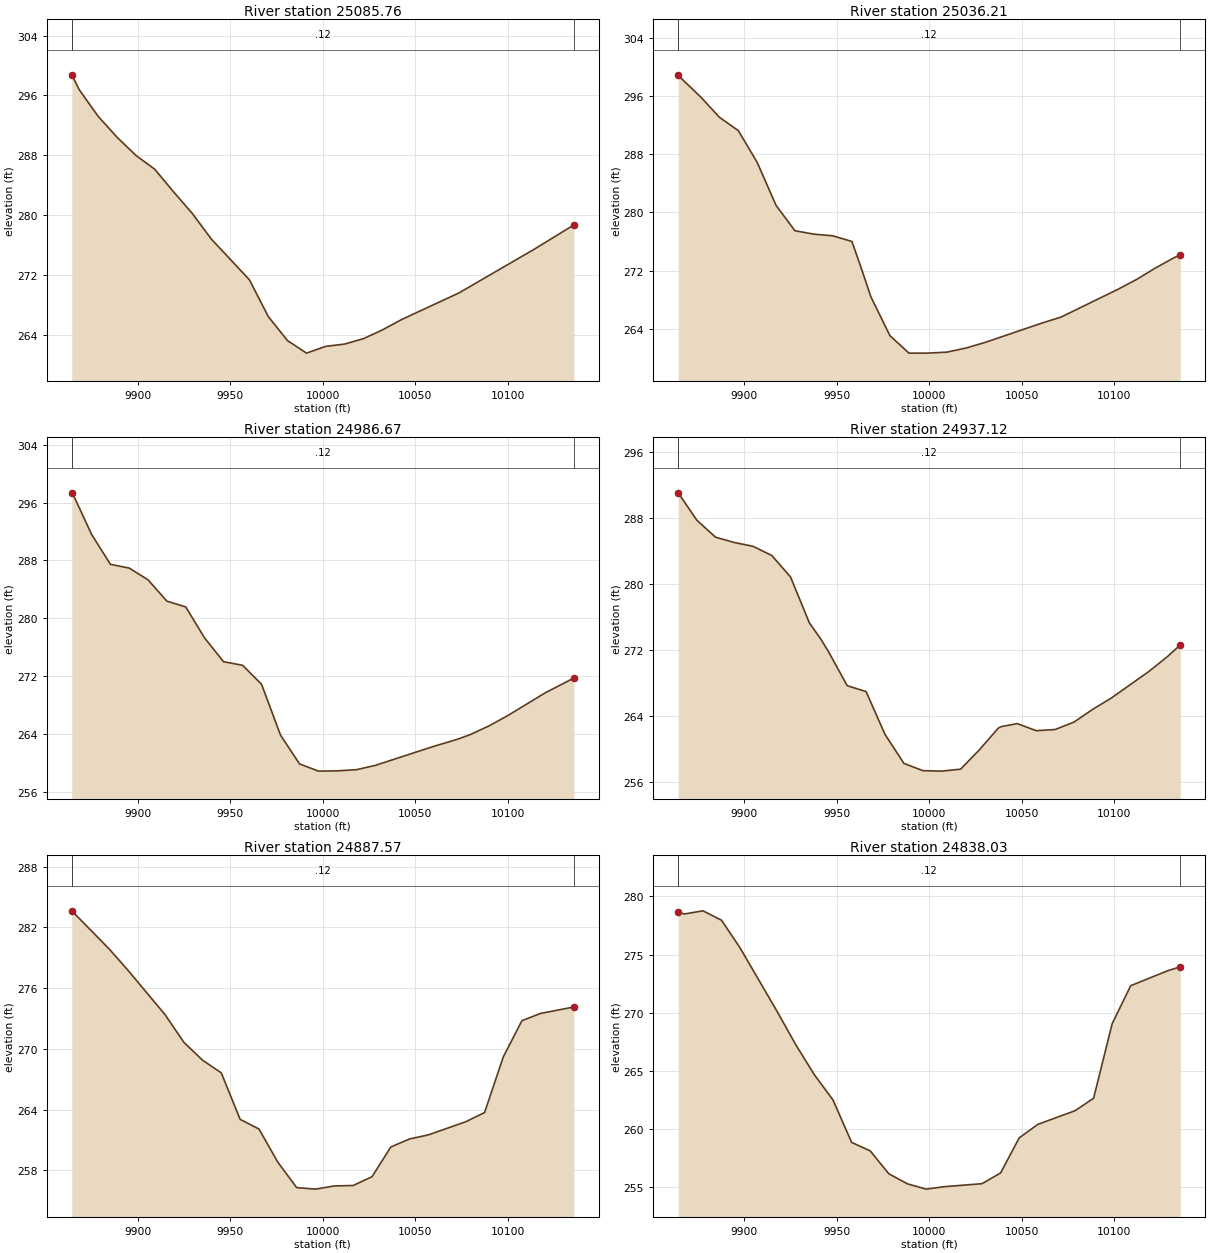
Type RM Length L Ch R = 1 ,25085.76,49.546400,49.546400,49.546400
XS GIS Cut Line= 6
 445552.64139562737111.028107267445567.207141549737184.945845162
445581.327174474737242.574440802445581.821181884737244.512469873
 445598.72436921737314.285765896445610.435639395737376.067588962
#Sta/Elev= 21
9864.328298.75759868.376296.76459878.568293.2089 9888.76290.41729898.953287.9843
9909.145286.13229919.337283.1025 9929.53280.19239939.723276.79439960.314271.3407
 9970.61266.38919980.906263.20239991.202 261.523 10001.5262.425310011.79262.7326
10022.08263.468610032.37264.647610042.66266.024110073.52 269.56810114.23275.4185
10135.67 278.675
#Mann= 3 , 0 , 0
9864.328    0.12       09864.328    0.12       010135.67    0.12       0
#XS Ineff= 2 , 0
       0                               0
Bank Sta=9864.328,10135.67
Exp/Cntr=0.3,0.1

Type RM Length L Ch R = 1 ,25036.21,49.546500,49.546500,49.546500
XS GIS Cut Line= 6
445504.859601665737123.095910919445518.237286224737191.204082627
445533.304647882737254.708475457445533.771393788737256.653250061
445550.152766779737326.552580307445561.857335645737388.337636319
#Sta/Elev= 26
9864.323298.88739866.264298.32439876.455295.85029886.646293.05049896.837291.2208
9907.028286.85419917.219280.9604 9927.41277.49279937.634277.02429947.912276.7936
9958.189276.01749963.027272.52619968.467268.41029978.744263.09329989.022260.6972
    9999260.697210009.57260.833510019.84261.397510030.11262.160910060.93264.8236
 10071.2265.640510101.75269.425810111.92270.7866 10122.1 272.35710132.28273.7903
10135.68274.1574
#Mann= 3 , 0 , 0
9864.323    0.12       09864.323    0.12       010135.68    0.12       0
#XS Ineff= 2 , 0
       0                               0
Bank Sta=9864.323,10135.68
Exp/Cntr=0.3,0.1

Type RM Length L Ch R = 1 ,24986.67,49.546400,49.546400,49.546400
XS GIS Cut Line= 6
445457.652961764737134.457801436445470.430065401 737202.68071243
445485.126311022737266.271276331445485.593056928737268.216050935
445501.431611953737338.238833256445512.512578119 737400.13931388
#Sta/Elev= 25
9864.324297.33829864.876297.1976 9875.05291.59459885.224287.45579895.397286.9396
9905.571285.31219915.745 282.3739925.919281.57429936.114277.29259946.377274.0023
9956.641273.51289966.904270.88679977.168263.85179987.432259.88269997.695258.8873
10007.96258.927910018.21259.087110028.46259.686510059.22262.250310072.79263.2915
10079.66263.932810089.82265.136210099.98266.5629 10120.3269.720410135.68271.7442
#Mann= 3 , 0 , 0
9864.324    0.12       09864.324    0.12       010135.68    0.12       0
#XS Ineff= 2 , 0
       0                               0
Bank Sta=9864.324,10135.68
Exp/Cntr=0.3,0.1

Type RM Length L Ch R = 1 ,24937.12,49.546500,49.546500,49.546500
XS GIS Cut Line= 6
445411.931095515737145.118672842445422.085565447737207.176385738
445436.879372044737277.428887506445437.301047788737279.383929595
445451.755856926737349.664718782445461.550627019737411.822188044
#Sta/Elev= 29
9864.324291.03149874.336287.72189884.469285.65379894.602285.01279904.735284.5473
9914.868283.43759925.001  280.849935.202275.2668 9941.35273.30169945.421271.8233
9955.641267.6517 9965.86 266.9329976.079261.74879986.299 258.2269996.518257.3475
10006.73257.289610016.94257.528210027.15259.887110037.36262.520510039.22262.7041
10047.57263.050510057.78262.196110067.99262.332810078.15263.228210088.28264.7709
 10098.4266.152910118.65269.365910128.77 271.18510135.68272.5957
#Mann= 3 , 0 , 0
9864.324    0.12       09864.324    0.12       010135.68    0.12       0
#XS Ineff= 2 , 0
       0                               0
Bank Sta=9864.324,10135.68
Exp/Cntr=0.3,0.1

Type RM Length L Ch R = 1 ,24887.57,49.546400,49.546400,49.546400
XS GIS Cut Line= 6
445367.282527748737154.945630568445377.155037401737229.630620977
445388.446676488737287.875155154445388.868352231737289.830197242
445400.770926064737353.726461258445409.432332739737422.856992751
#Sta/Elev= 24
9864.336283.63829884.565279.86899894.652277.77689914.826273.36319924.913270.6463
    9935 268.881 9945.14 267.6289955.327263.03359965.513262.07729975.699258.8009
9985.885256.28779996.071256.138210006.26256.452210016.43256.4967 10026.6257.3639
10036.77260.305210046.95261.097610057.12261.502110077.36262.805510087.44263.7058
10097.51269.192810107.59 272.77810117.67273.501610135.67274.1337
#Mann= 3 , 0 , 0
9864.336    0.12       09864.336    0.12       010135.67    0.12       0
#XS Ineff= 2 , 0
       0                               0
Bank Sta=9864.336,10135.67
Exp/Cntr=0.3,0.1

Type RM Length L Ch R = 1 ,24838.03,49.546500,49.546500,49.546500
XS GIS Cut Line= 6
445326.895065039737161.650935045445331.287618673737224.377564872
445339.680617882737295.679436193445339.906437257737297.666646703
445348.389057908737374.690239737445352.157469403737431.756033676
#Sta/Elev= 25
9864.326278.62299867.683278.47839877.707278.75029887.732277.94219897.756275.5693
9917.805270.10299927.833267.26189937.902 264.6769947.971262.5134 9958.04258.8688
9968.109258.13749978.178  256.179988.247255.30799998.316254.856310008.38255.0701
 10028.5255.321610038.56256.247510048.62259.261110058.68260.4176 10078.8261.5887
10088.82262.662610098.84269.053310108.87272.321410128.91273.609710135.68273.9426
#Mann= 3 , 0 , 0
9864.326    0.12       09864.326    0.12       010135.68    0.12       0
#XS Ineff= 2 , 0
       0                               0
Bank Sta=9864.326,10135.68
Exp/Cntr=0.3,0.1

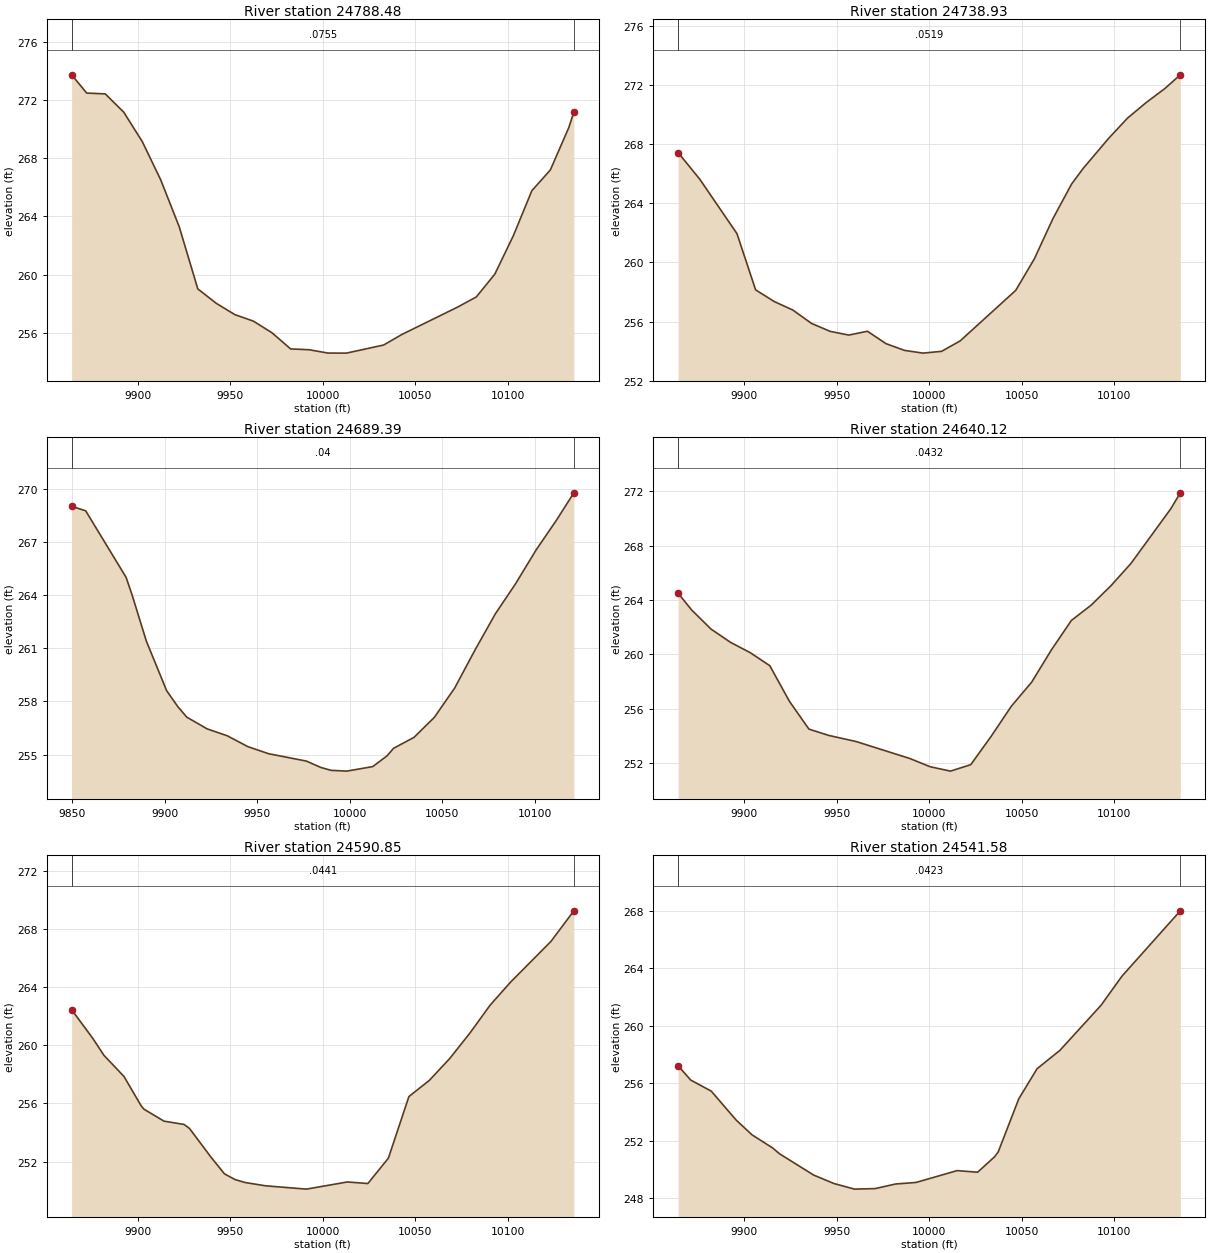
Type RM Length L Ch R = 1 ,24788.48,49.546400,49.546400,49.546400
XS GIS Cut Line= 6
 445285.95109424737166.858967166445285.259796065737242.184600906
445290.451006819737301.273710158445290.676826194737303.260920668
445295.518018396737355.920412695445296.341791714737437.687861676
#Sta/Elev= 26
9864.354273.73859872.496272.48269882.496272.42789892.497271.16969902.497269.1503
9912.498 266.5069922.498263.27719932.498 259.013 9942.51258.01669952.548257.2409
9962.587256.79199972.625255.98939982.664254.88219992.702254.825710002.75 254.598
10012.79254.593110032.87255.149510042.92255.886410072.96 257.76610082.96258.4591
10092.96260.025510102.96262.667310112.96 265.76510122.96267.193410132.97270.1216
10135.65 271.175
#Mann= 3 , 0 , 0
9864.354  0.0755       09864.354  0.0755       010135.65  0.0755       0
#XS Ineff= 2 , 0
       0                               0
Bank Sta=9864.354,10135.65
Exp/Cntr=0.3,0.1

Type RM Length L Ch R = 1 ,24738.93,49.546500,49.546500,49.546500
XS GIS Cut Line= 6
445254.504801993737173.404089179445242.949604579737273.929046655
445241.269353672737307.356265158445241.514857924 737309.34113988
 445238.57825405737361.580588042445228.719402988737443.305574384
#Sta/Elev= 25
9864.344267.43019876.016265.63659896.148261.94459906.213258.14249916.279257.3523
9926.345256.77499936.411255.87149946.477255.33369956.543255.08249966.603255.3418
9976.616254.50449986.628254.04649996.641253.860810006.67253.982310016.68254.6847
10046.73258.107710056.77260.236210066.84262.965310076.91265.3056 10083.2266.3665
10097.06268.414810107.13269.7657 10117.2  270.8210127.27271.763810135.64272.6956
#Mann= 3 , 0 , 0
9864.344  0.0519       09864.344  0.0519       010135.64  0.0519       0
#XS Ineff= 2 , 0
       0                               0
Bank Sta=9864.344,10135.64
Exp/Cntr=0.3,0.1

Type RM Length L Ch R = 1 ,24689.39,49.270500,49.270500,49.270500
XS GIS Cut Line= 6
445258.193741412737158.062396315445223.613733634737236.415742537
445201.458447849737280.149836492445200.489816084737281.899622909
445181.964922198737317.760271152445142.728290997737403.525512217
#Sta/Elev= 28
9849.783 269.0029857.366 268.7499879.227264.9921 9882.46263.99849890.158261.3991
9901.088258.61179907.227257.69599912.019257.1134 9922.95 256.455 9933.88256.0632
9945.051255.44979956.261 255.0529976.617254.63829984.454254.27729989.943254.1162
9998.415254.071710012.45254.3267 10020.2 254.93210023.71 255.35710034.78255.9761
10045.77257.103310056.77258.760710067.77260.909210078.76262.946110089.76 264.655
10100.76266.543510111.76268.222310121.13269.7622
#Mann= 3 , 0 , 0
9849.783    0.04       09849.783    0.04       010121.13    0.04       0
#XS Ineff= 2 , 0
       0                               0
Bank Sta=9849.783,10121.13
Exp/Cntr=0.3,0.1

Type RM Length L Ch R = 1 ,24640.12,49.270500,49.270500,49.270500
XS GIS Cut Line= 6
445197.883449577737148.148335093445173.438938548737219.400037579
445149.429984129737273.645546856445148.555205638737275.444091432
445126.598143938737323.975361529445096.956658214737399.792730417
#Sta/Elev= 24
9864.351264.50879871.594263.28549882.166261.86519892.739260.88769903.311260.1344
9913.883 259.1759924.455256.56319935.027254.50959945.803254.0424 9960.53253.5946
9989.545252.346810000.51 251.74110011.49251.417510022.46251.892910033.44253.9716
10044.42256.199210055.37 257.965 10066.1 260.35410076.84262.505310087.58 263.639
10098.32265.075810109.05266.705510130.53 270.72110135.67271.8939
#Mann= 3 , 0 , 0
9864.351  0.0432       09864.351  0.0432       010135.67  0.0432       0
#XS Ineff= 2 , 0
       0                               0
Bank Sta=9864.351,10135.67
Exp/Cntr=0.3,0.1

Type RM Length L Ch R = 1 ,24590.85,49.270400,49.270400,49.270400
XS GIS Cut Line= 6
445159.402108359 737128.88998025445130.529790677737198.477594077
445105.122398632737252.095164803445104.247620141737253.893709379
 445078.94008002737306.840324061445048.091362924737376.296995363
#Sta/Elev= 26
9864.328262.44099875.815  260.469881.769259.30699892.596257.85759901.909255.8313
9903.422255.60469914.249254.78269925.076254.55689928.003254.28269939.667 252.302
9946.885251.16469952.581250.77149957.951250.56859969.017250.34219991.149250.1122
10013.31250.603810024.39250.497110035.48 252.24110046.56256.473110057.64257.5894
10068.61259.085710079.55  260.84 10090.5262.762810101.44264.328610123.32267.1348
10135.68269.2356
#Mann= 3 , 0 , 0
9864.328  0.0441       09864.328  0.0441       010135.68  0.0441       0
#XS Ineff= 2 , 0
       0                               0
Bank Sta=9864.328,10135.68
Exp/Cntr=0.3,0.1

Type RM Length L Ch R = 1 ,24541.58,49.270500,49.270500,49.270500
XS GIS Cut Line= 4
445118.451386353737108.823223259445060.814813135737230.544782751
445059.940034645737232.343327327445001.271995404737353.579974792
#Sta/Elev= 23
9864.322257.20519871.156256.21229882.221255.44519895.754253.4222 9904.35252.3931
9915.414  251.49 9919.12251.08369937.543249.60399948.607  249.019959.672248.6239
9970.736 248.6599981.801248.97989992.865 249.08810015.06249.911810026.17249.8016
 10035.3250.871410037.28251.208510048.39254.902610058.26257.000810070.61258.2789
10092.83261.414110104.17263.445710135.69267.9929
#Mann= 3 , 0 , 0
9864.322  0.0423       09864.322  0.0423       010135.69  0.0423       0
#XS Ineff= 2 , 0
       0                               0
Bank Sta=9864.322,10135.69
Exp/Cntr=0.3,0.1

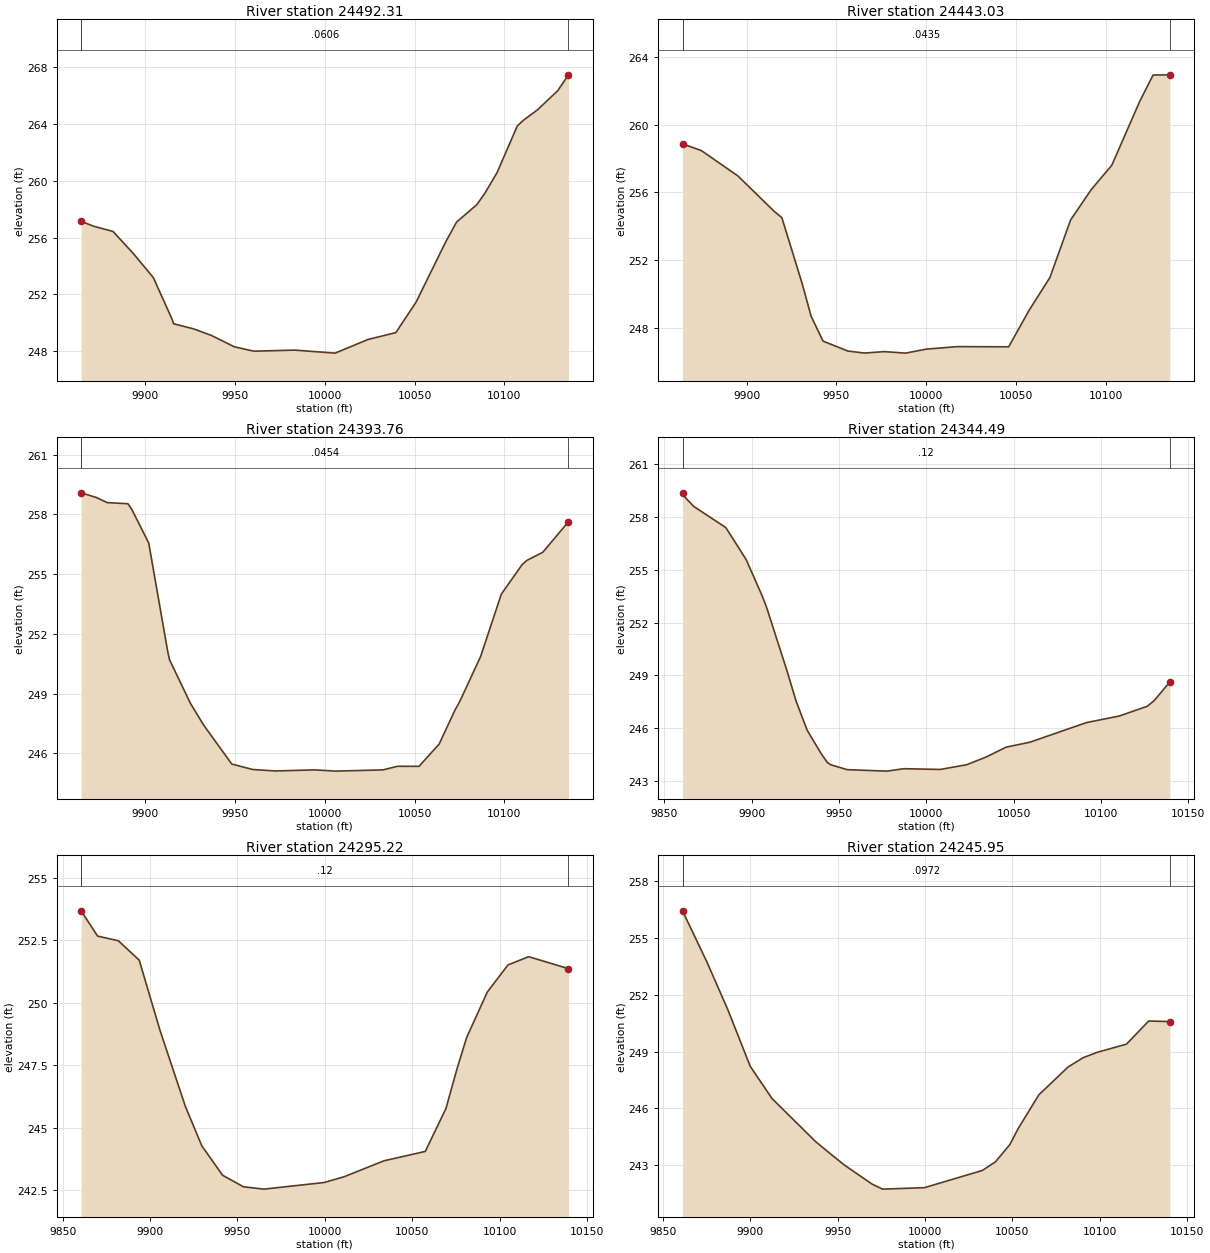
Type RM Length L Ch R = 1 ,24492.31,49.270500,49.270500,49.270500
XS GIS Cut Line= 4
445078.201988085737089.274962003445016.507227639737208.994400698
445015.632449148737210.792945274 444953.49677128737330.288297663
#Sta/Elev= 27
9864.319 257.1419871.309256.79589882.009256.43519893.259254.89449904.509253.1887
9914.969250.25929915.758249.94669927.008 249.581  9936.8249.12579949.508248.3316
 9958.63248.06639960.757248.01819983.257248.091710005.74  247.8810024.05248.8397
10039.56249.322310050.83251.4684 10067.4255.718310073.37 257.09110084.64258.3136
10089.07 259.10610095.91260.563810107.18263.846510110.75264.258410118.45264.9808
10129.72 266.32610135.68267.4363
#Mann= 3 , 0 , 0
9864.319  0.0606       09864.319  0.0606       010135.68  0.0606       0
#XS Ineff= 2 , 0
       0                               0
Bank Sta=9864.319,10135.68
Exp/Cntr=0.3,0.1

Type RM Length L Ch R = 1 ,24443.03,49.270500,49.270500,49.270500
XS GIS Cut Line= 4
445040.114241561737066.807315441444974.061640324737184.167555684
444973.039489538737185.886627461444906.749920526737303.119311327
#Sta/Elev= 23
9864.329258.85859874.756258.46999895.144256.96959915.533254.8615 9919.63 254.508
9931.105250.55819935.921248.6886 9942.58247.2152 9956.31 246.631 9965.53 246.511
9976.698246.5952 9988.48246.50619999.968 246.74110017.33  246.8910045.93246.8789
10057.42249.053210068.91250.9735 10080.4254.364510091.89256.158310103.37257.6023
10118.92261.371910126.35 262.92510135.68262.9373
#Mann= 3 , 0 , 0
9864.329  0.0435       09864.329  0.0435       010135.68  0.0435       0
#XS Ineff= 2 , 0
       0                               0
Bank Sta=9864.329,10135.68
Exp/Cntr=0.3,0.1

Type RM Length L Ch R = 1 ,24393.76,49.270500,49.270500,49.270500
XS GIS Cut Line= 4
444999.200281243 737042.43111867444931.711886695737158.986621096
444930.689735909737160.705692872444863.422461355737277.389348701
#Sta/Elev= 27
9864.316259.08169872.698258.84959878.839258.59149890.395258.53379892.655258.2275
 9901.95256.55829912.611251.07119913.506 250.7039925.061248.52949932.568 247.414
9948.172245.46429959.727245.19019972.481245.11499994.393245.169910005.96245.1069
10032.41245.169710040.58245.351510052.44245.346710063.67246.467410072.46248.1698
10075.21248.614910086.76250.8665 10098.3 253.99810109.84255.4754 10112.5255.6881
10121.38256.096810135.68257.6322
#Mann= 3 , 0 , 0
9864.316  0.0454       09864.316  0.0454       010135.68  0.0454       0
#XS Ineff= 2 , 0
       0                               0
Bank Sta=9864.316,10135.68
Exp/Cntr=0.3,0.1

Type RM Length L Ch R = 1 ,24344.49,49.270500,49.270500,49.270500
XS GIS Cut Line= 6
444958.264953205737013.699793635444917.708677994737081.817004082
444889.362133066737133.805686507444888.339982281737135.524758284
444860.706227993737186.986902834444820.419510636737256.194409286
#Sta/Elev= 26
9860.509259.37899862.022259.12059866.891258.60839885.299 257.4049896.937 255.586
9905.986253.55049908.575  252.899920.214249.29629925.533247.53689931.852245.8864
9939.786 244.5689943.411244.05029945.444243.91799954.801243.64269977.581243.5588
9987.223243.696310008.06243.653910023.11 243.92110034.46244.365310045.81244.9243
10059.41245.203310091.83  246.3210110.51246.690310126.54247.245110130.39 247.556
10139.49248.6262
#Mann= 3 , 0 , 0
9860.509    0.12       09860.509    0.12       010139.49    0.12       0
#XS Ineff= 2 , 0
       0                               0
Bank Sta=9860.509,10139.49
Exp/Cntr=0.3,0.1

Type RM Length L Ch R = 1 ,24295.22,49.275500,49.275500,49.275500
XS GIS Cut Line= 6
 444917.50157588 736997.13427111444864.098274042737079.265970671
444843.948017594737114.397269731 444843.17477728737116.241747819
444827.180671147737145.286732967444770.840440351737234.263996372
#Sta/Elev= 21
9860.533253.66839869.915252.65939881.843252.47189893.771251.6971  9905.7248.8852
9920.156245.85939929.556244.28219941.484243.10229953.412242.6413 9965.11242.5476
9999.654242.8123   10011243.041410033.83243.679110057.49244.053810069.33245.7688
10075.62247.345410081.16248.6039   10093250.421610104.83251.505910116.67251.8359
10139.47251.3576
#Mann= 3 , 0 , 0
9860.533    0.12       09860.533    0.12       010139.47    0.12       0
#XS Ineff= 2 , 0
       0                               0
Bank Sta=9860.533,10139.47
Exp/Cntr=0.3,0.1

Type RM Length L Ch R = 1 ,24245.95,49.343200,49.343200,49.343200
XS GIS Cut Line= 6
444890.396830424736973.804351658444840.160003849737041.814203538
444806.076216866 737083.61420562444804.780612747737085.137823016
444773.764383381737122.851852793444720.168181147737194.725192063
#Sta/Elev= 22
 9861.19256.44289875.109253.74949887.104251.22279899.974248.22129912.406246.5234
9937.271244.25349945.743243.60549953.908242.99979969.732241.99669975.659241.7317
9999.677241.808510032.82 242.71910040.34243.176610048.56 244.08610053.19244.9107
10065.17246.7172 10081.9248.187310090.61248.683310098.62248.964910115.35249.3962
10128.03250.617310140.16250.5899
#Mann= 3 , 0 , 0
 9861.19  0.0972       0 9861.19  0.0972       010140.16  0.0972       0
#XS Ineff= 2 , 0
       0                               0
Bank Sta=9861.19,10140.16
Exp/Cntr=0.3,0.1