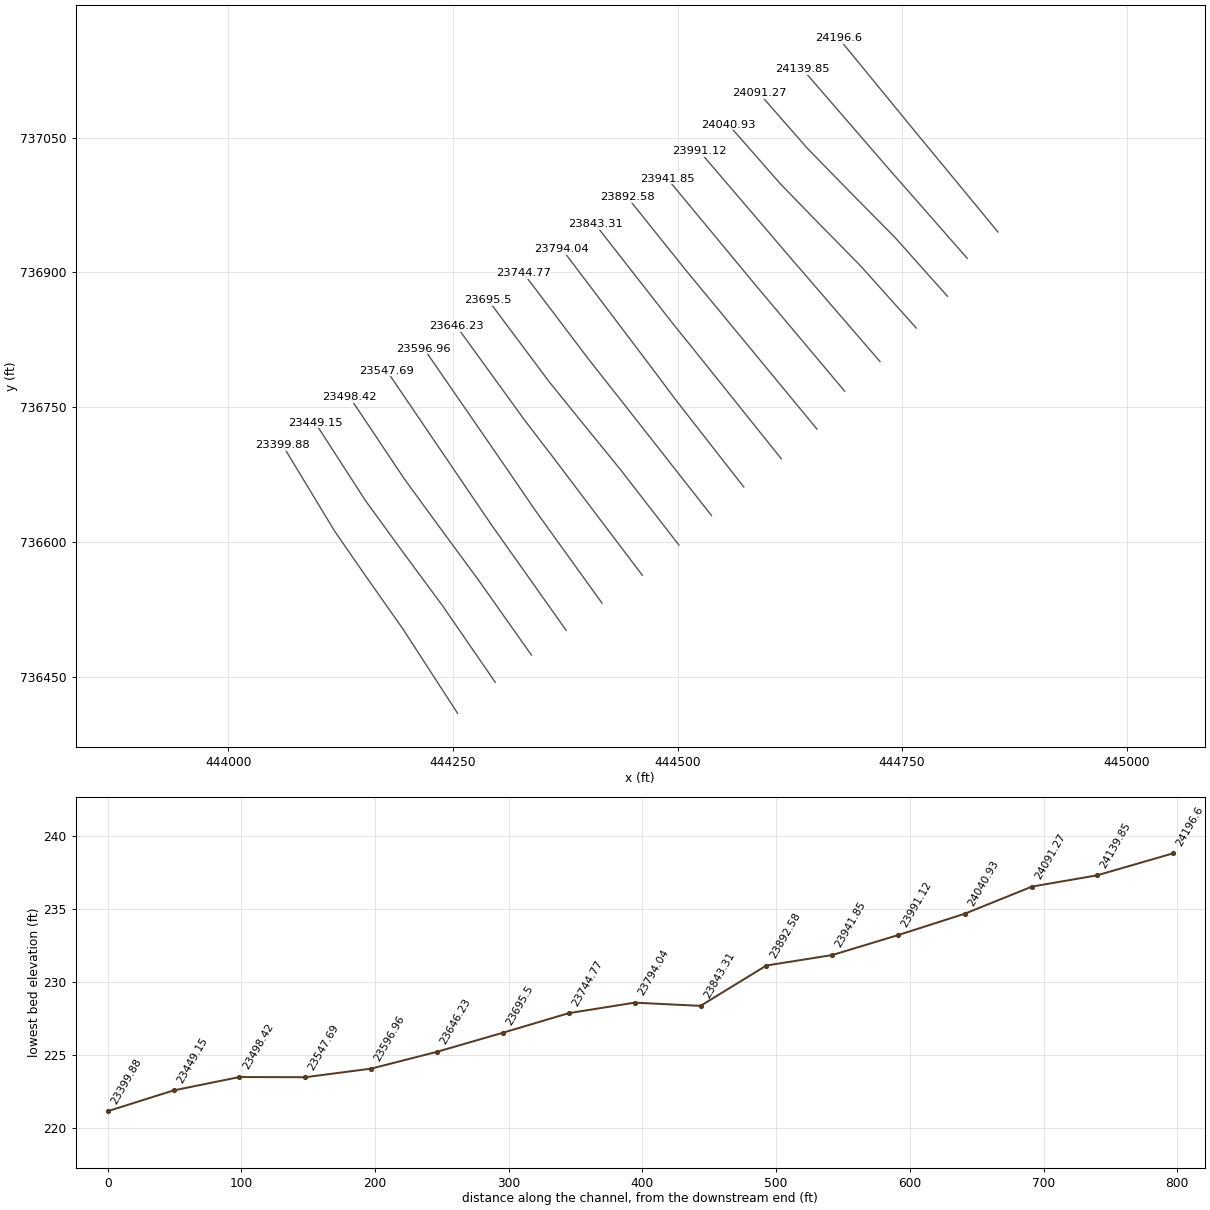
HEC-RAS study 708_ras.prj: 708

--- 708_ras.g01 (geometry) --- (continued)

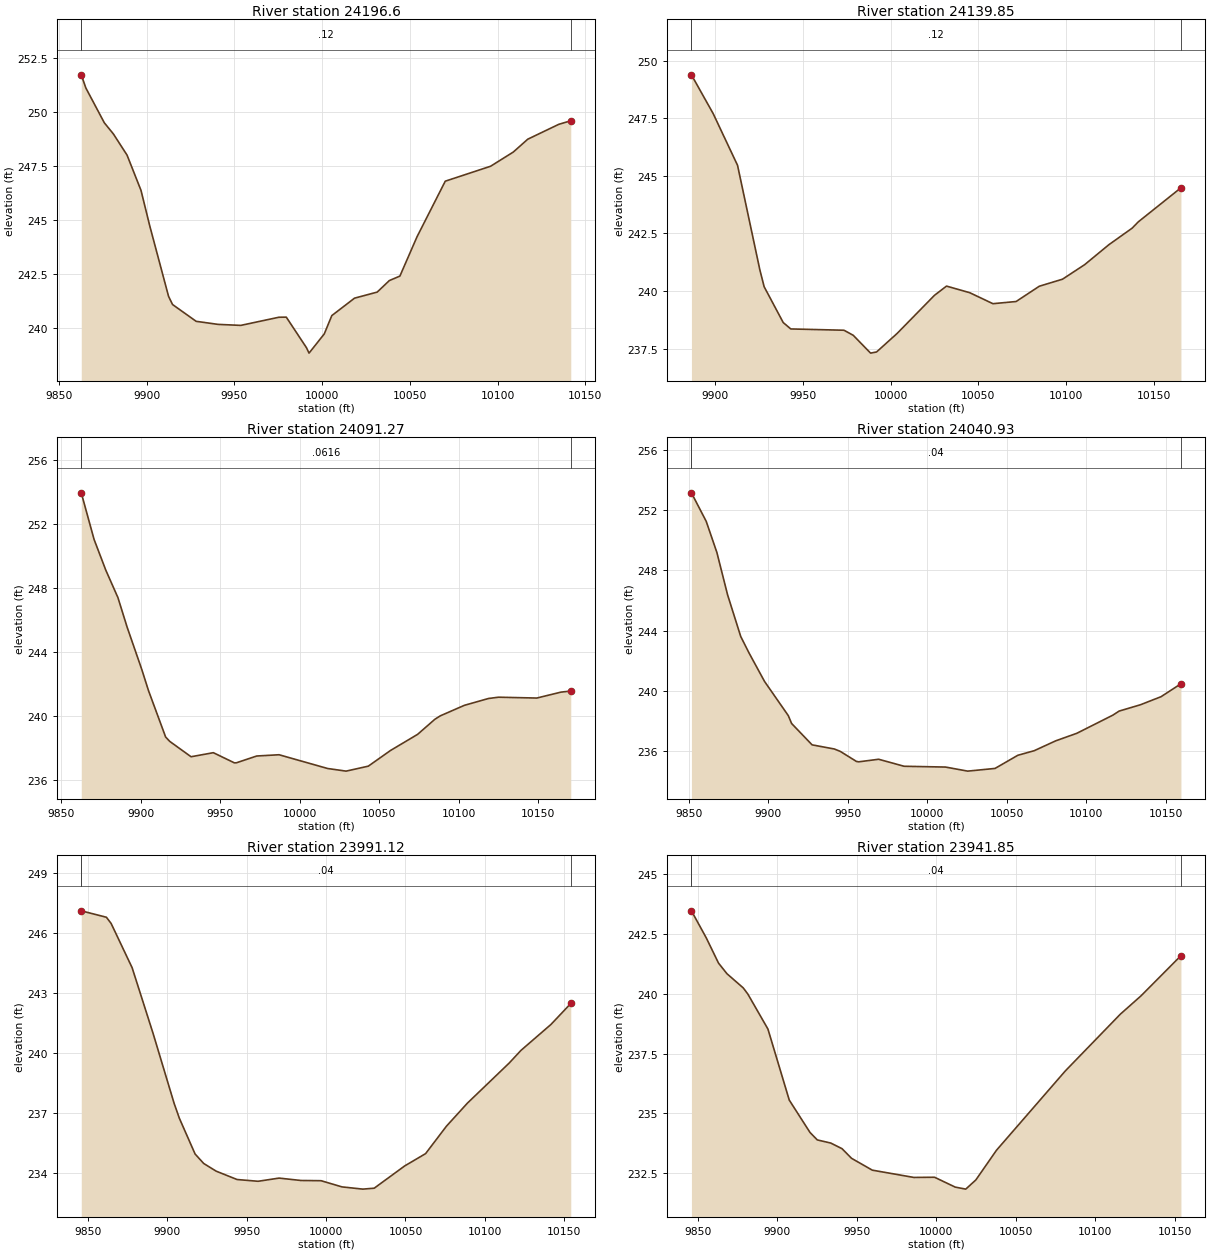
Type RM Length L Ch R = 1 , 24196.6,56.759400,56.759400,56.759400
XS GIS Cut Line= 4
444856.657902762736944.863194575444768.541529699737051.696681304
444767.245925581  737053.2202987444679.463613713737160.326261487
#Sta/Elev= 29
9862.683251.73459865.289251.12549875.823249.50699881.005248.98819888.786248.0052
9896.721246.36959901.748244.71059912.437241.44669914.711241.06859928.153240.2884
9940.636240.14629953.599240.09979975.301240.47769979.524240.48279991.017239.0639
9992.487238.811610001.17239.704710005.47240.5546 10018.4241.363310031.33241.6457
10038.26242.181310044.26242.388510054.04244.216110070.12246.795410095.97247.4899
 10108.9248.149310117.14248.745610134.76 249.43410141.65249.6016
#Mann= 3 , 0 , 0
9862.683    0.12       09862.683    0.12       010141.65    0.12       0
#XS Ineff= 2 , 0
       0                               0
Bank Sta=9862.683,10141.65
Exp/Cntr=0.3,0.1

Type RM Length L Ch R = 1 ,24139.85,48.579000,48.579000,48.579000
XS GIS Cut Line= 4
 444822.33501152736915.675212986444731.006842532737019.779156988
444729.711238414737021.302774384444639.125732944737126.051632602
#Sta/Elev= 24
9886.496249.3829  9898.9247.69919912.782245.45649925.505240.91659927.945240.1868
9938.808 238.6349943.109 238.3569973.436238.29999978.716238.0805  9988.6237.3066
9992.019 237.35710003.76238.163510024.98239.813110031.87 240.21510045.09239.9294
10058.31239.451910071.53239.545910084.75240.209210097.97240.514410110.62241.1465
10124.41 242.01210137.64242.7279 10141.2243.004510165.47 244.481
#Mann= 3 , 0 , 0
9886.496    0.12       09886.496    0.12       010165.47    0.12       0
#XS Ineff= 2 , 0
       0                 10032.4       0
Bank Sta=9886.496,10165.47
Exp/Cntr=0.3,0.1

Type RM Length L Ch R = 1 ,24091.27,50.338700,50.338700,50.338700
XS GIS Cut Line= 6
444800.369225555  736873.4875897444741.904727296736938.913947087
 444695.99029981736985.294943749 444694.56096228736986.693869846
444644.395105209737038.042486411444590.922710509737099.173326192
#Sta/Elev= 28
 9862.64253.93969870.698251.02649878.079249.10349885.706247.3891 9891.49245.5429
9900.714242.89679904.901241.58499915.722238.67079918.312238.39729931.723237.4357
9945.737  237.699958.946237.05619960.197237.05639973.018237.48239987.089237.5612
10017.65236.701410029.26 236.53710043.24236.847310057.22237.827710074.26238.8354
10085.18 239.78310088.57239.9951 10103.7240.651510118.89241.079310125.25241.1595
10149.27241.106810164.46241.476210170.65241.5464
#Mann= 3 , 0 , 0
 9862.64  0.0616       0 9862.64  0.0616       010170.65  0.0616       0
#XS Ineff= 2 , 0
       0                               0
Bank Sta=9862.64,10170.65
Exp/Cntr=0.3,0.1

Type RM Length L Ch R = 1 ,24040.93,49.805600,49.805600,49.805600
XS GIS Cut Line= 6
444765.710288771736838.076001468444703.142941876736907.795348678
444661.527413288736950.082864122444660.098075758736951.481790218
444614.626341436736998.292459227444556.728623435737064.224285023
#Sta/Elev= 28
 9851.58253.15119860.883251.25989867.615249.18649874.319246.38719882.588243.6188
9887.756242.5355 9897.56240.63529912.532 238.3629914.628237.83769927.504236.4206
9941.501236.14599945.257235.98629955.365235.32269956.866235.29479969.396235.4645
 9985.38234.999410011.49234.946510025.43234.676610042.61234.855110056.96235.7288
10067.26236.031410080.77236.686910094.08237.188110116.75238.3928 10120.7238.6626
10134.01239.078410147.06239.616910159.59240.4757
#Mann= 3 , 0 , 0
 9851.58    0.04       0 9851.58    0.04       010159.59    0.04       0
#XS Ineff= 2 , 0
       0                               0
Bank Sta=9851.58,10159.59
Exp/Cntr=0.3,0.1

Type RM Length L Ch R = 1 ,23991.12,49.270500,49.270500,49.270500
XS GIS Cut Line= 4
444725.346349005736800.784041967444625.334577582736916.594950903
444624.052298776736918.129799776444524.641216746737034.455623881
#Sta/Elev= 26
9845.982247.13249861.812246.81069864.765246.50229877.978244.28929891.191240.9955
9904.403 237.5059907.712236.75569917.616234.96799923.012234.49529930.829234.1115
9944.042233.69169957.254233.60359970.467233.76289984.212233.64379996.893233.6321
10010.04 233.32310023.19233.211210030.33233.2579 10049.5234.371310062.65234.9862
10075.81236.362610088.96237.511210115.27239.518210122.68240.151510141.58241.4511
10154.02242.4968
#Mann= 3 , 0 , 0
9845.982    0.04       09845.982    0.04       010154.02    0.04       0
#XS Ineff= 2 , 0
       0                               0
Bank Sta=9845.982,10154.02
Exp/Cntr=0.3,0.1

Type RM Length L Ch R = 1 ,23941.85,49.270500,49.270500,49.270500
XS GIS Cut Line= 4
444685.968614945736767.856349273 444587.52320022736885.005698916
444586.240921414736886.540547789444488.579908935737004.342820778
#Sta/Elev= 24
9845.979243.4623 9855.31242.33489863.028241.27959868.372240.83429878.572240.2451
9881.434239.99269894.116238.52739907.558235.5585 9920.62234.20679925.203233.8966
9933.682233.76539940.747233.53149946.744233.12849959.806232.6342 9985.93232.3305
9998.993232.337710011.99231.926310018.61231.842210024.98232.227510037.97233.4674
10081.29236.7793 10115.9 239.14810128.89239.911910154.02241.5896
#Mann= 3 , 0 , 0
9845.979    0.04       09845.979    0.04       010154.02    0.04       0
#XS Ineff= 2 , 0
       0                               0
Bank Sta=9845.979,10154.02
Exp/Cntr=0.3,0.1

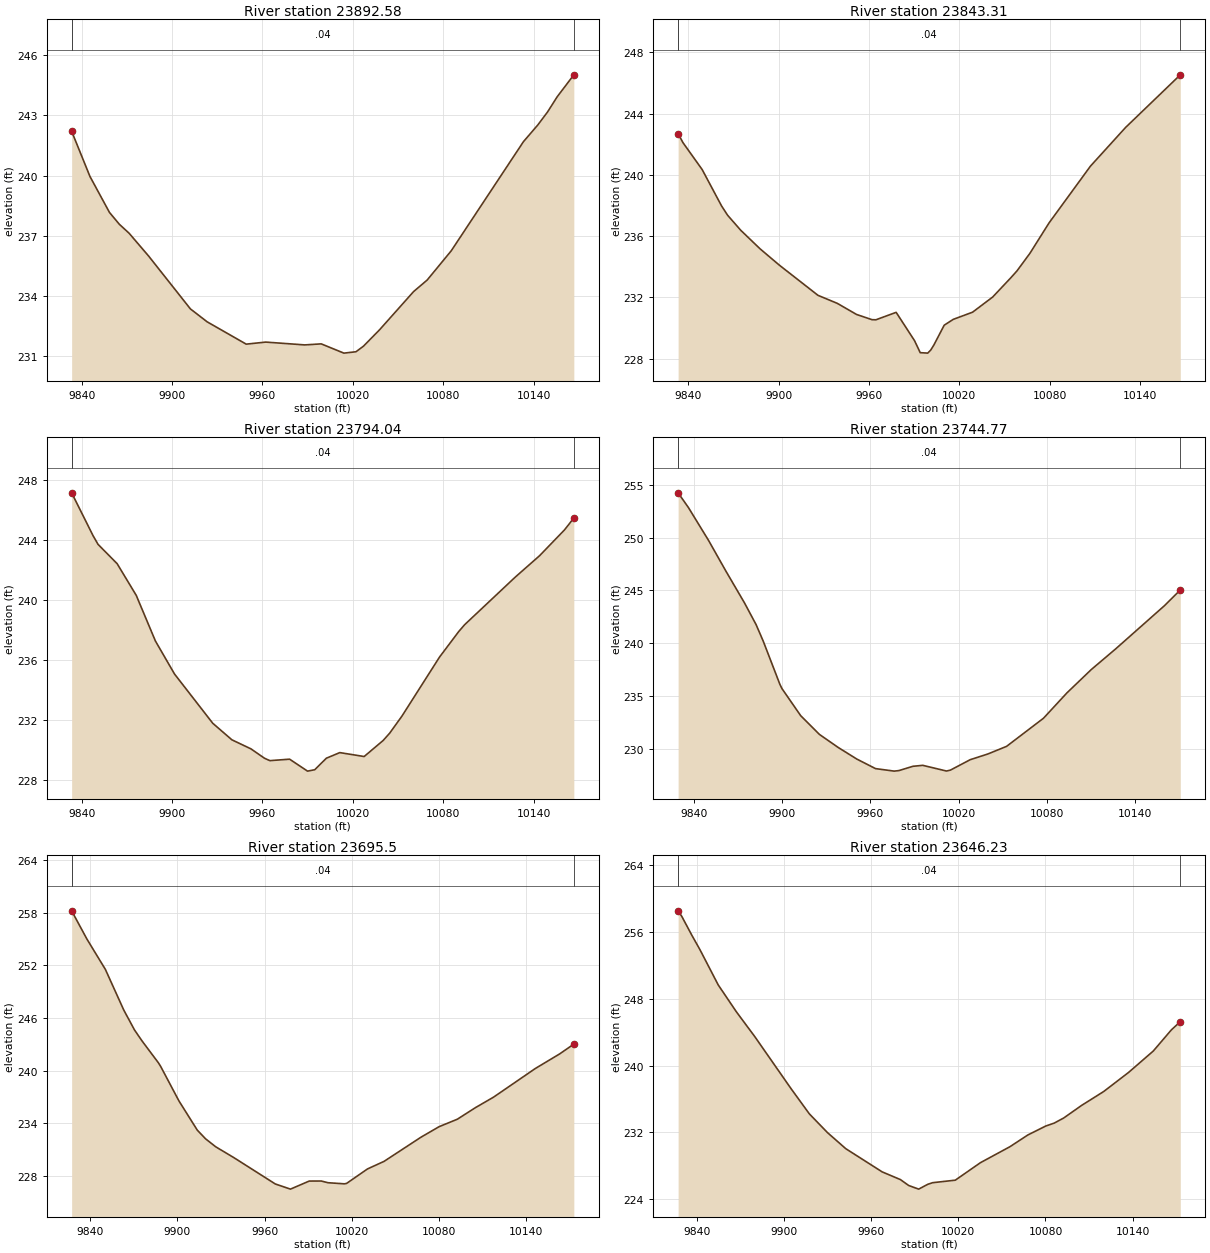
Type RM Length L Ch R = 1 ,23892.58,49.270500,49.270500,49.270500
XS GIS Cut Line= 5
444655.173524696736725.636682946444549.711822857736853.416446928
444548.429544051736854.951295801444510.605793043736900.667292399
444444.080558582736983.634781664
#Sta/Elev= 24
 9833.32242.21099845.461239.95429858.427238.15589865.013237.56089871.393237.1214
9884.359235.98119912.142233.33569923.257232.68919949.189 231.5749962.155231.6765
9988.087231.5356    9999231.587210014.04 231.12510022.07 231.19410027.02231.4712
10037.75232.293710060.33234.2016 10069.3234.774910085.28236.236210133.24241.6918
10142.79242.527810149.22243.173810155.61243.931710166.68245.0306
#Mann= 3 , 0 , 0
 9833.32    0.04       0 9833.32    0.04       010166.68    0.04       0
#XS Ineff= 2 , 0
       0                               0
Bank Sta=9833.32,10166.68
Exp/Cntr=0.3,0.1

Type RM Length L Ch R = 1 ,23843.31,49.270500,49.270500,49.270500
XS GIS Cut Line= 5
444615.526191404736692.553465412444511.900445495736821.827194941
444510.618166689736823.362043814444494.814688472736842.943495894
 444408.24184731736953.623159554
#Sta/Elev= 30
 9833.32242.69159836.455242.11119849.271240.34419862.088237.98069866.138237.3637
9874.904236.3776 9887.72235.16759900.536   234.19926.169232.13099938.985231.6071
9951.801230.88059962.068230.54139964.618230.53379978.056231.0203 9990.25229.1732
9994.044228.3881    9999228.3576   10001228.5558 10003.1228.889910009.95230.1801
10015.96230.561610028.77231.029610042.09232.016110054.17233.275810058.32233.7338
10066.86234.874310079.56236.860310107.02 240.56310130.34243.088210166.68246.5265
#Mann= 3 , 0 , 0
 9833.32    0.04       0 9833.32    0.04       010166.68    0.04       0
#XS Ineff= 2 , 0
       0                               0
Bank Sta=9833.32,10166.68
Exp/Cntr=0.3,0.1

Type RM Length L Ch R = 1 ,23794.04,49.270500,49.270500,49.270500
XS GIS Cut Line= 5
444573.756671249 736661.21081488444499.151203481736756.602390751
444472.414046539736792.272706992444471.226341944736793.881855151
444371.234016965736925.984270156
#Sta/Elev= 28
 9833.32247.11669847.534244.26299850.826243.68539863.521242.39669876.216240.2837
9888.911 237.2499901.606 235.0479926.997231.76539939.692230.66379952.387230.0586
9961.343229.43549964.916229.27639978.016229.37429989.911228.57799994.688228.6708
 10002.4229.438410011.32229.811710027.49 229.55110040.03230.613110044.45231.1086
10052.57232.242210077.59236.185110090.19237.865210094.16238.328710127.82241.5049
10143.87242.921510160.44244.642610166.68245.4395
#Mann= 3 , 0 , 0
 9833.32    0.04       0 9833.32    0.04       010166.68    0.04       0
#XS Ineff= 2 , 0
       0                               0
Bank Sta=9833.32,10166.68
Exp/Cntr=0.3,0.1

Type RM Length L Ch R = 1 ,23744.77,49.270500,49.270500,49.270500
XS GIS Cut Line= 5
444537.763007201736629.485392106 444432.92224141736762.913915395
444431.645096472736764.453038784444401.287936993736802.962377096
444328.451050328736899.147607621
#Sta/Elev= 29
 9829.31254.24929836.323252.85249849.967249.74569861.758 246.8349874.476243.8017
9882.338241.74749887.194240.17589898.524236.07739899.912235.68359912.629233.1187
9925.347231.34279938.065230.10789950.782229.0031  9963.5228.09679976.218 227.858
9979.452227.91089988.935228.31639995.637228.406810011.73227.867510014.43227.9552
10027.89228.9432 10039.9229.485610052.59230.206310077.68232.872310093.58235.2719
10110.15237.486410126.71239.444810159.84 243.53710170.69245.0361
#Mann= 3 , 0 , 0
 9829.31    0.04       0 9829.31    0.04       010170.69    0.04       0
#XS Ineff= 2 , 0
       0                               0
Bank Sta=9829.31,10170.69
Exp/Cntr=0.3,0.1

Type RM Length L Ch R = 1 , 23695.5,49.270500,49.270500,49.270500
XS GIS Cut Line= 6
444501.514009852736596.660495228444436.227395264736680.849685986
 444395.00556032736731.451137479444393.728415381736732.990260867
  444356.4253623 736779.12938094444289.118348559736869.230586755
#Sta/Elev= 30
9827.196 258.2259837.749254.99599850.404251.55279863.058246.92339870.463244.6486
9875.713 243.3839886.781240.93789888.367240.52549901.022236.56859913.676233.2325
9919.418232.23869926.331231.34049939.086230.07739967.343227.10319977.781 226.515
9990.679227.4338    9999227.438510003.58227.245510014.88227.118210016.44227.1689
10030.79228.815210042.16229.675110067.66232.437810080.14233.635710092.62234.4804
10105.11235.801610117.59236.999710146.26240.255310162.97241.9134 10172.8243.0375
#Mann= 3 , 0 , 0
9827.196    0.04       09827.196    0.04       0 10172.8    0.04       0
#XS Ineff= 2 , 0
       0                               0
Bank Sta=9827.196,10172.8
Exp/Cntr=0.3,0.1

Type RM Length L Ch R = 1 ,23646.23,49.270500,49.270500,49.270500
XS GIS Cut Line= 5
444460.794965107 736563.01774932 444357.08887923736699.988359562
444355.811734291 736701.52748295444328.751956663736736.950530939
444254.084477904736839.958360176
#Sta/Elev= 30
9827.198258.52249829.684257.87259836.798255.54949842.227253.8732 9854.77249.6622
9867.313246.43029879.856243.49179904.942237.23089917.485234.22329930.028231.9669
9942.571230.05169967.657227.2696  9980.2226.34859985.894 225.6419992.743225.2081
    9999225.784510002.34225.976710017.95226.280510035.28228.376510055.52230.2824
10067.87 231.68910080.22232.761810086.05233.113510092.57233.723910104.92235.2337
10120.12 236.89710137.16239.1701 10154.2241.738910166.68244.2769 10172.8245.2557
#Mann= 3 , 0 , 0
9827.198    0.04       09827.198    0.04       0 10172.8    0.04       0
#XS Ineff= 2 , 0
       0                               0
Bank Sta=9827.198,10172.8
Exp/Cntr=0.3,0.1

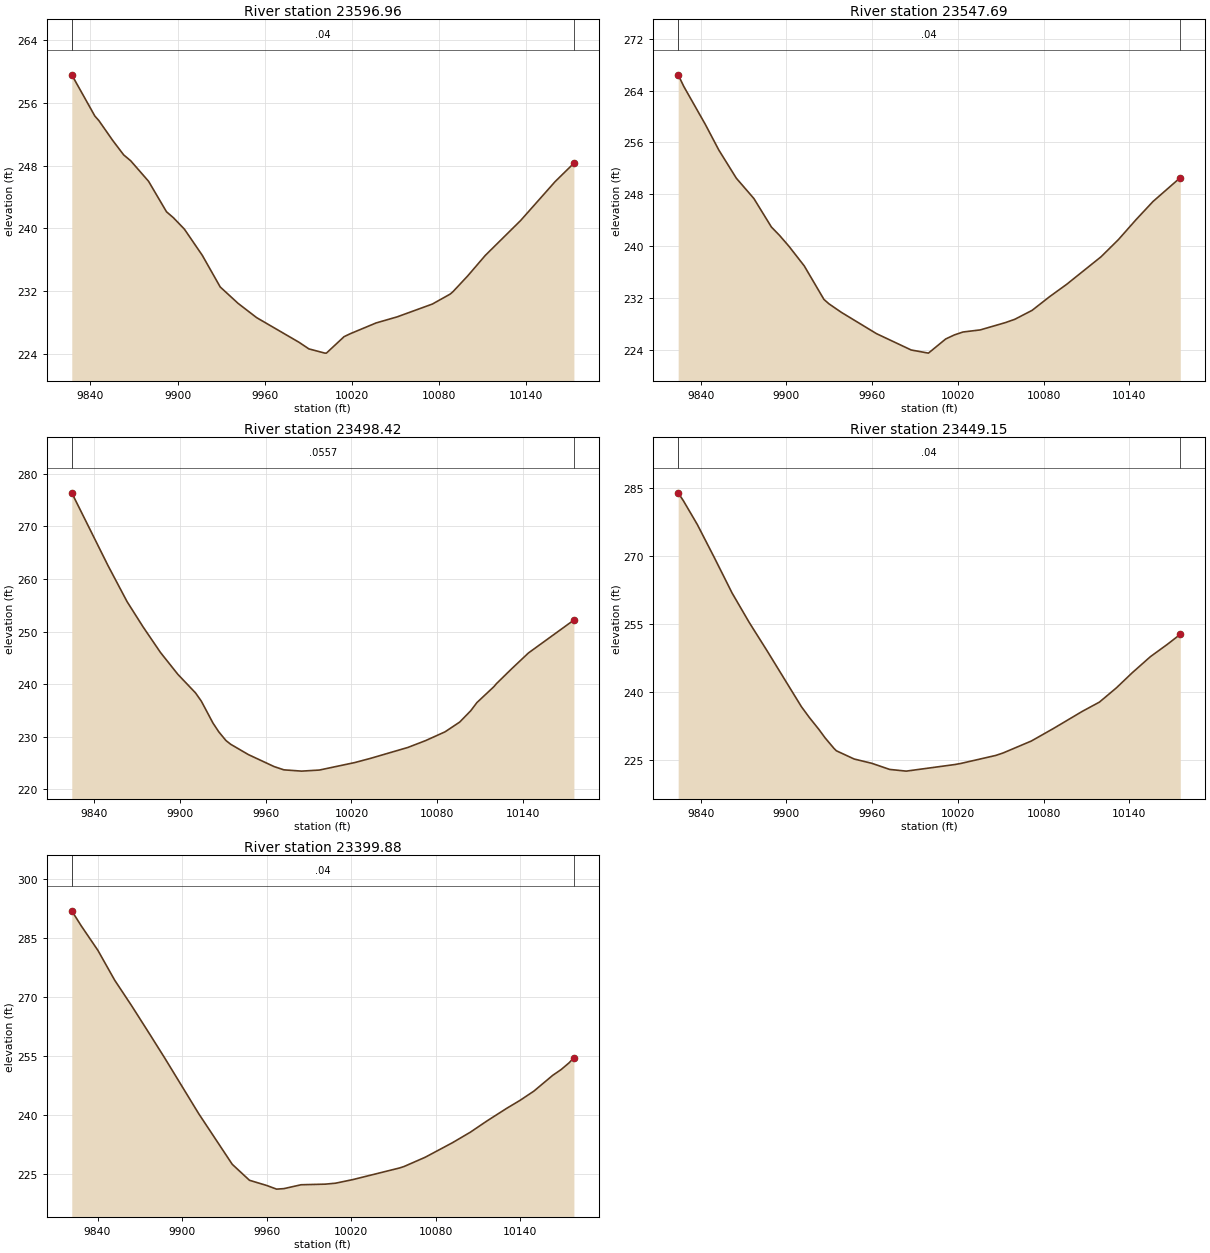
Type RM Length L Ch R = 1 ,23596.96,49.270500,49.270500,49.270500
XS GIS Cut Line= 5
444415.875821882736532.094602918444341.514565573 736635.32674157
444316.353277869736672.125530489444315.237282689736673.785215627
444217.659767154736815.189980072
#Sta/Elev= 30
9827.195259.5737  9843.1254.30849845.803253.74319855.425 251.1899862.912249.3585
9867.749 248.6049880.021245.99479892.397242.09479897.131241.33799904.722239.8776
9917.046 236.533 9929.37232.49689941.695230.40139954.422228.58649983.681225.4307
9990.368224.597110001.42224.054710002.48224.059910014.63226.157710019.02226.5434
10036.63227.905110051.08 228.67810075.37230.316710087.52231.574510089.45231.8735
10099.67233.902410111.82236.525610136.12240.977610159.88245.9462 10172.8248.2919
#Mann= 3 , 0 , 0
9827.195    0.04       09827.195    0.04       0 10172.8    0.04       0
#XS Ineff= 2 , 0
       0                               0
Bank Sta=9827.195,10172.8
Exp/Cntr=0.3,0.1

Type RM Length L Ch R = 1 ,23547.69,49.270400,49.270400,49.270400
XS GIS Cut Line= 5
444376.012845852736501.773966382444292.601879164 736619.46415623
444275.466528589736644.632716292444274.350533409 736646.29240143
444176.166612878 736790.78857946
#Sta/Elev= 30
9824.301266.43969828.255264.63599843.347258.76639852.769 254.8189865.026250.4681
9877.282247.34049889.539242.93929895.229241.64699901.796 239.9739912.523236.9369
 9926.31  231.769929.817231.07859938.567229.7527 9963.08226.47259987.347223.9517
9999.443223.465410011.53 225.65210017.64226.280810023.62226.726810035.71227.0513
10053.22228.173910059.89228.690710071.98 230.06910084.07232.157710096.16234.0862
10120.34238.364310132.43241.003510144.52244.024910156.61 246.883 10175.7250.5649
#Mann= 3 , 0 , 0
9824.301    0.04       09824.301    0.04       0 10175.7    0.04       0
#XS Ineff= 2 , 0
       0                               0
Bank Sta=9824.301,10175.7
Exp/Cntr=0.3,0.1

Type RM Length L Ch R = 1 ,23498.42,49.270500,49.270500,49.270500
XS GIS Cut Line= 6
444337.313690758 736474.29251693444277.948211643736558.345501195
  444235.3577003736616.141340114444234.153515947736617.738193283
444195.702437624736670.473863348 444134.87251556 736761.42915719
#Sta/Elev= 30
9824.303276.35199849.654262.53379862.981255.6885 9874.14250.90799886.383 246.017
9898.625241.83969910.868238.35199914.983236.76199923.111232.61269927.206 230.934
9932.176229.29589935.473228.58439947.895226.6182 9965.89224.34179972.738223.7221
 9985.16223.47689997.582223.681410022.36225.104410033.51225.913510059.49 227.975
10071.71229.253610085.52230.942910095.77232.796810103.51234.9519 10107.8236.4961
10119.83239.555610121.49240.096910131.86242.848210143.89245.929410175.69252.1821
#Mann= 3 , 0 , 0
9824.303  0.0557       09824.303  0.0557       010175.69  0.0557       0
#XS Ineff= 2 , 0
       0                               0
Bank Sta=9824.303,10175.69
Exp/Cntr=0.3,0.1

Type RM Length L Ch R = 1 ,23449.15,49.270500,49.270500,49.270500
XS GIS Cut Line= 6
444297.061676593736443.997266533444238.683228993736528.735477302
444196.018831955 736586.47596406444194.814647601736588.072817228
  444152.5746108736646.120339153444096.771340384736732.562954104
#Sta/Elev= 30
9824.306283.8332 9827.94282.09239837.667 276.8749849.811269.44979861.954261.8173
9874.097255.25559886.241249.19629910.528236.75389916.073234.37499922.671231.7858
9927.207229.84759933.405 227.5369934.996227.0404 9947.43225.22949959.864224.2736
9972.297222.93529983.887222.559210017.68224.000310021.93224.235810046.67226.0249
10051.67226.5555 10071.4 229.18310086.76231.917510107.16235.729910119.07237.7512
10130.97240.895410142.07 244.22710154.77247.763910166.68250.487710175.68 252.685
#Mann= 3 , 0 , 0
9824.306    0.04       09824.306    0.04       010175.68    0.04       0
#XS Ineff= 2 , 0
       0                               0
Bank Sta=9824.306,10175.68
Exp/Cntr=0.3,0.1

Type RM Length L Ch R = 1 ,23399.88,49.270500,49.270500,49.270500
XS GIS Cut Line= 6
444255.180957305736409.423056418444194.212538406 736503.42217995
444156.679963609736556.810588006444155.475779255736558.407441174
 444118.33863154736612.066113395444060.283420097736707.876349761
#Sta/Elev= 30
9821.699  291.839828.346288.05459840.265281.78179852.185274.20489864.104 267.776
9877.162 260.4399887.942254.30679911.781240.33439935.668227.43599947.891223.3827
9960.115222.06169967.145221.13329972.339  221.269984.533 222.24210001.84222.3991
10009.02222.642110021.18223.543410054.55226.514810057.66226.8784 10072.7229.2327
   10092232.917610104.76235.599910116.46 238.43210130.59241.668110139.84243.6385
10149.89246.038110163.23250.038210169.18251.498510174.92253.235210178.28 254.537
#Mann= 3 , 0 , 0
9821.699    0.04       09821.699    0.04       010178.28    0.04       0
#XS Ineff= 2 , 0
       0                               0
Bank Sta=9821.699,10178.28
Exp/Cntr=0.3,0.1