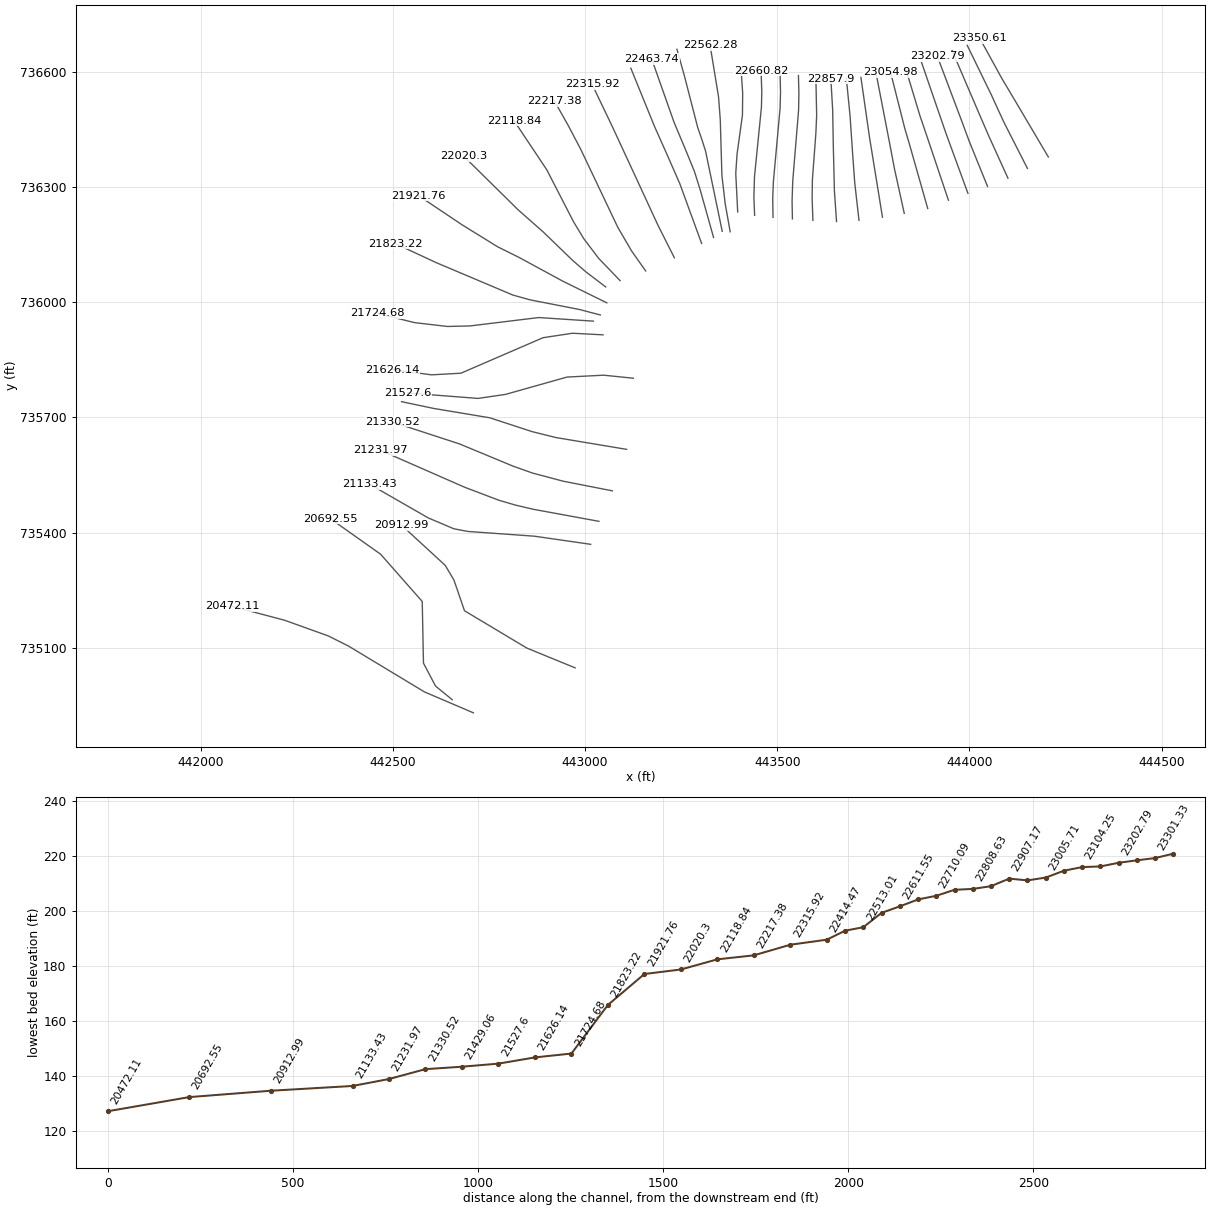
HEC-RAS study 708_ras.prj: 708

--- 708_ras.g01 (geometry) --- (continued)

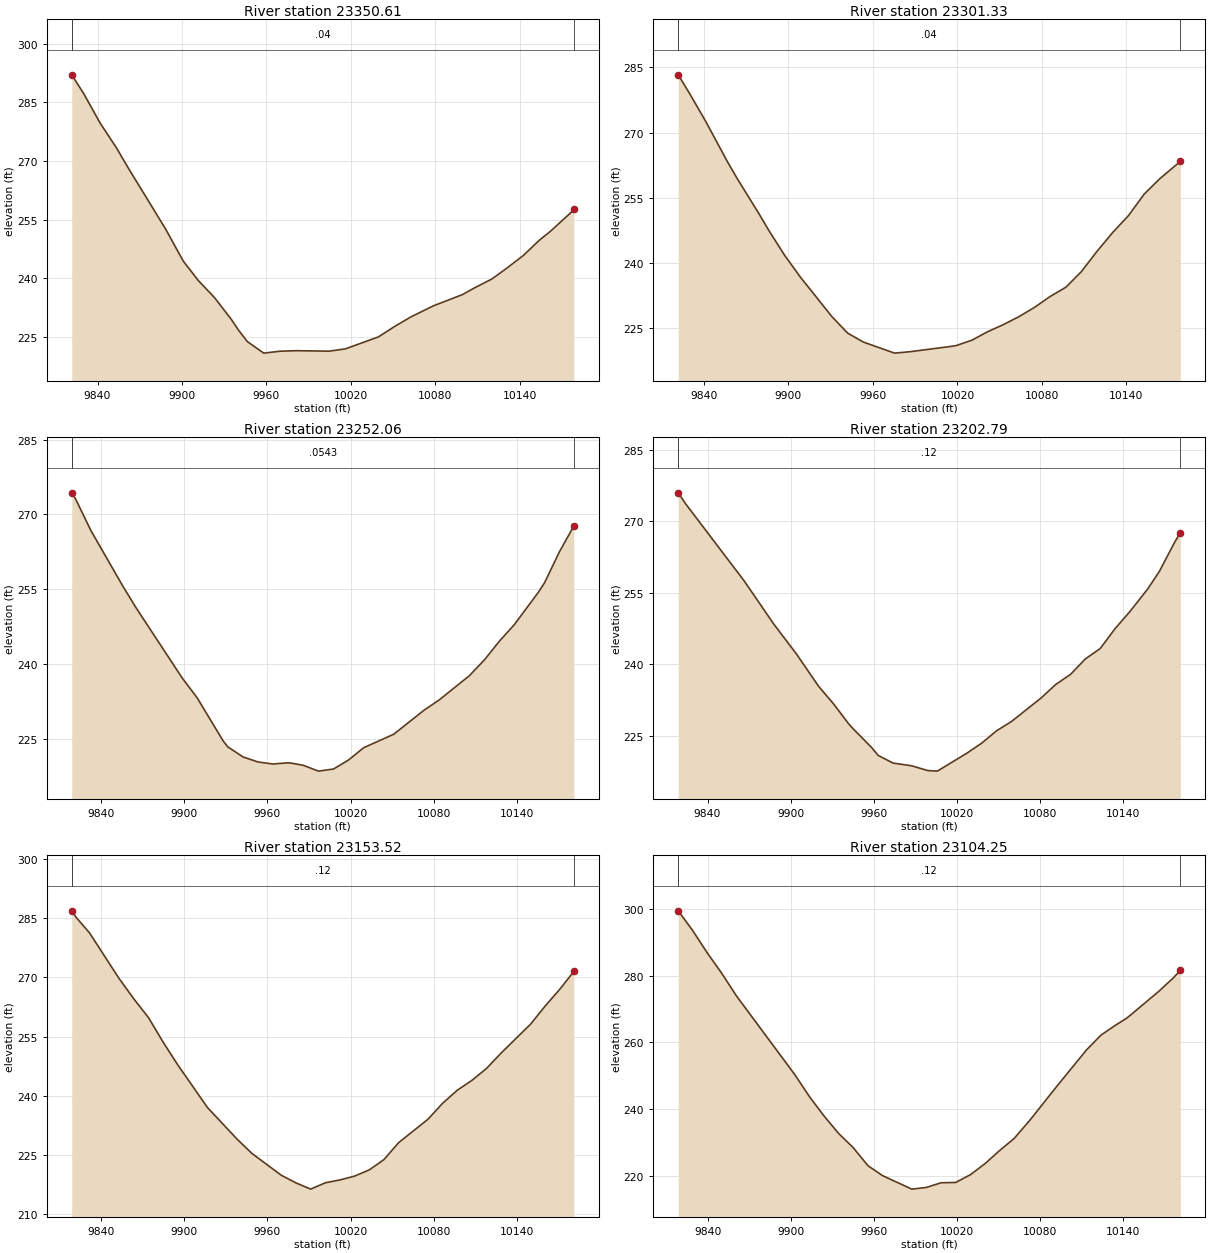
Type RM Length L Ch R = 1 ,23350.61,49.270500,49.270500,49.270500
XS GIS Cut Line= 5
 444205.30396321736377.612404732  444115.1029252736530.262117434
444114.060025182736531.968681102444083.743070875736582.971525728
444026.929402018736686.359663507
#Sta/Elev= 30
9821.692 292.0689830.273287.20299841.888279.69929853.504273.35449861.603268.3616
 9888.35252.62179900.917244.3977 9911.58239.44959923.196235.03239934.811229.5995
9940.231 226.7119946.426223.82649958.042220.87549969.657221.36649981.273221.4978
10004.53221.375410016.16221.979910039.43225.013210051.06227.705710062.65230.1573
10078.49232.962910099.25235.861210108.29237.672210120.02239.818410131.11242.7229
10142.52245.885510153.93249.804810161.54 251.99810176.75257.0083 10178.3257.6317
#Mann= 3 , 0 , 0
9821.692    0.04       09821.692    0.04       0 10178.3    0.04       0
#XS Ineff= 2 , 0
       0                               0
Bank Sta=9821.692,10178.3
Exp/Cntr=0.3,0.1

Type RM Length L Ch R = 1 ,23301.33,49.270500,49.270500,49.270500
XS GIS Cut Line= 6
444150.933038317736347.788791363 444090.68647091736466.059400489
444071.910238195736506.485434571444071.118055972736508.321856997
444057.235141291736538.799261952443994.241699322736668.088595915
#Sta/Elev= 30
9821.695283.29129829.788278.98189841.011272.69589856.798263.21539863.456259.4975
9878.829251.44529885.901247.57279897.124 241.8439908.347236.80789930.792227.6962
9942.015223.88019953.237221.8156 9975.31 219.2739986.336219.600810015.76220.8355
10019.33221.033810030.32222.252310041.39224.185810052.51225.813510063.64227.6518
10074.76229.798710085.88232.310710097.01234.426310108.09238.039110119.25 242.735
10130.38247.0536 10141.5250.903210152.63255.842610163.75 259.39510178.31263.3691
#Mann= 3 , 0 , 0
9821.695    0.04       09821.695    0.04       010178.31    0.04       0
#XS Ineff= 2 , 0
       0                               0
Bank Sta=9821.695,10178.31
Exp/Cntr=0.3,0.1

Type RM Length L Ch R = 1 ,23252.06,49.270500,49.270500,49.270500
XS GIS Cut Line= 5
444100.187445911736322.496050796   444050.199616736432.531353238
444026.669522614736486.969831765444025.877340391736488.806254191
443954.957290516736654.427664012
#Sta/Elev= 30
9818.836274.31379821.587273.0916 9832.57266.77919855.556255.64989865.521 251.117
9898.471237.17769909.455233.11069928.088224.51529931.422223.33319942.383221.3061
9953.277220.28839964.172219.87789975.066220.13039978.004220.0196 9985.96219.6186
9996.854218.452210007.74218.876910018.62220.690810029.49223.146710051.25225.8656
10073.01230.669510083.89232.719410105.64237.574710116.52240.7437 10127.4244.5248
10138.28247.876210155.65 254.38610160.03256.258610170.91262.551710181.17 267.663
#Mann= 3 , 0 , 0
9818.836  0.0543       09818.836  0.0543       010181.17  0.0543       0
#XS Ineff= 2 , 0
       0                               0
Bank Sta=9818.836,10181.17
Exp/Cntr=0.3,0.1

Type RM Length L Ch R = 1 ,23202.79,49.270500,49.270500,49.270500
XS GIS Cut Line= 5
444047.072301954736301.081435084 443999.62347637736418.045388472
443980.895486062736468.628045951443980.232997052736470.515135857
443916.683579145736639.096168217
#Sta/Elev= 30
 9818.84275.92399824.352273.55239866.235257.52859887.818248.38389904.158242.1194
9920.192235.32389930.759231.72069941.775227.49379945.062 226.4389958.378222.5104
9963.141220.85229973.804219.24689987.179218.6765    9999217.670610005.79217.5519
10027.17221.317910037.85223.422710048.54226.003610059.23 227.942 10080.6232.8694
10091.29235.730510101.98237.851110112.66241.095410123.35243.252910134.04247.4224
10144.72250.999510157.58255.7369 10166.1259.463110176.78 265.39710181.16267.5812
#Mann= 3 , 0 , 0
 9818.84    0.12       0 9818.84    0.12       010181.16    0.12       0
#XS Ineff= 2 , 0
       0                               0
Bank Sta=9818.84,10181.16
Exp/Cntr=0.3,0.1

Type RM Length L Ch R = 1 ,23153.52,49.270500,49.270500,49.270500
XS GIS Cut Line= 5
443996.125875109736283.046464984443942.015111665  736430.7336823
443934.406564718 736452.30746718443933.744075708736454.194557086
443875.156809725 736624.56891194
#Sta/Elev= 30
9818.836286.94349822.109285.22869831.567281.38399852.867269.80629863.517264.6152
9874.167259.82319884.817253.55269895.467247.72859916.767236.95829938.067228.9496
9948.717  225.339970.017219.74979980.648217.79969991.251216.218610001.85217.8381
10012.43 218.558   10023219.534810033.58221.114610044.15223.737810054.73228.0328
10075.87233.971710086.45 238.02810097.02 241.344 10107.6243.856710118.17246.8926
10128.75250.8279 10149.9258.121110160.47262.743510171.05267.019410181.17271.5397
#Mann= 3 , 0 , 0
9818.836    0.12       09818.836    0.12       010181.17    0.12       0
#XS Ineff= 2 , 0
       0                               0
Bank Sta=9818.836,10181.17
Exp/Cntr=0.3,0.1

Type RM Length L Ch R = 1 ,23104.25,49.270400,49.270400,49.270400
XS GIS Cut Line= 5
 443945.37454108736265.230457302443887.917643374736435.986888408
443887.255154364736437.873978314443871.468446647736484.299115457
443833.547613157736609.821747077
#Sta/Elev= 30
9818.836299.51089829.144293.66469839.695286.95439850.246280.75929860.797274.0063
    9903250.3206 9914.08 243.4219924.102237.93359934.653232.66689945.204228.3946
9955.755223.02129966.306220.03469987.408215.98859997.959216.502410008.53217.8966
10019.09217.995110029.65220.309510040.21223.629710050.77227.573210061.21231.1747
 10072.4236.567710092.55247.117210113.45257.755410123.89262.199710134.34265.1741
10141.56267.038410144.79268.070210165.68275.365310176.14279.385110181.16281.6609
#Mann= 3 , 0 , 0
9818.836    0.12       09818.836    0.12       010181.16    0.12       0
#XS Ineff= 2 , 0
       0                               0
Bank Sta=9818.836,10181.16
Exp/Cntr=0.3,0.1

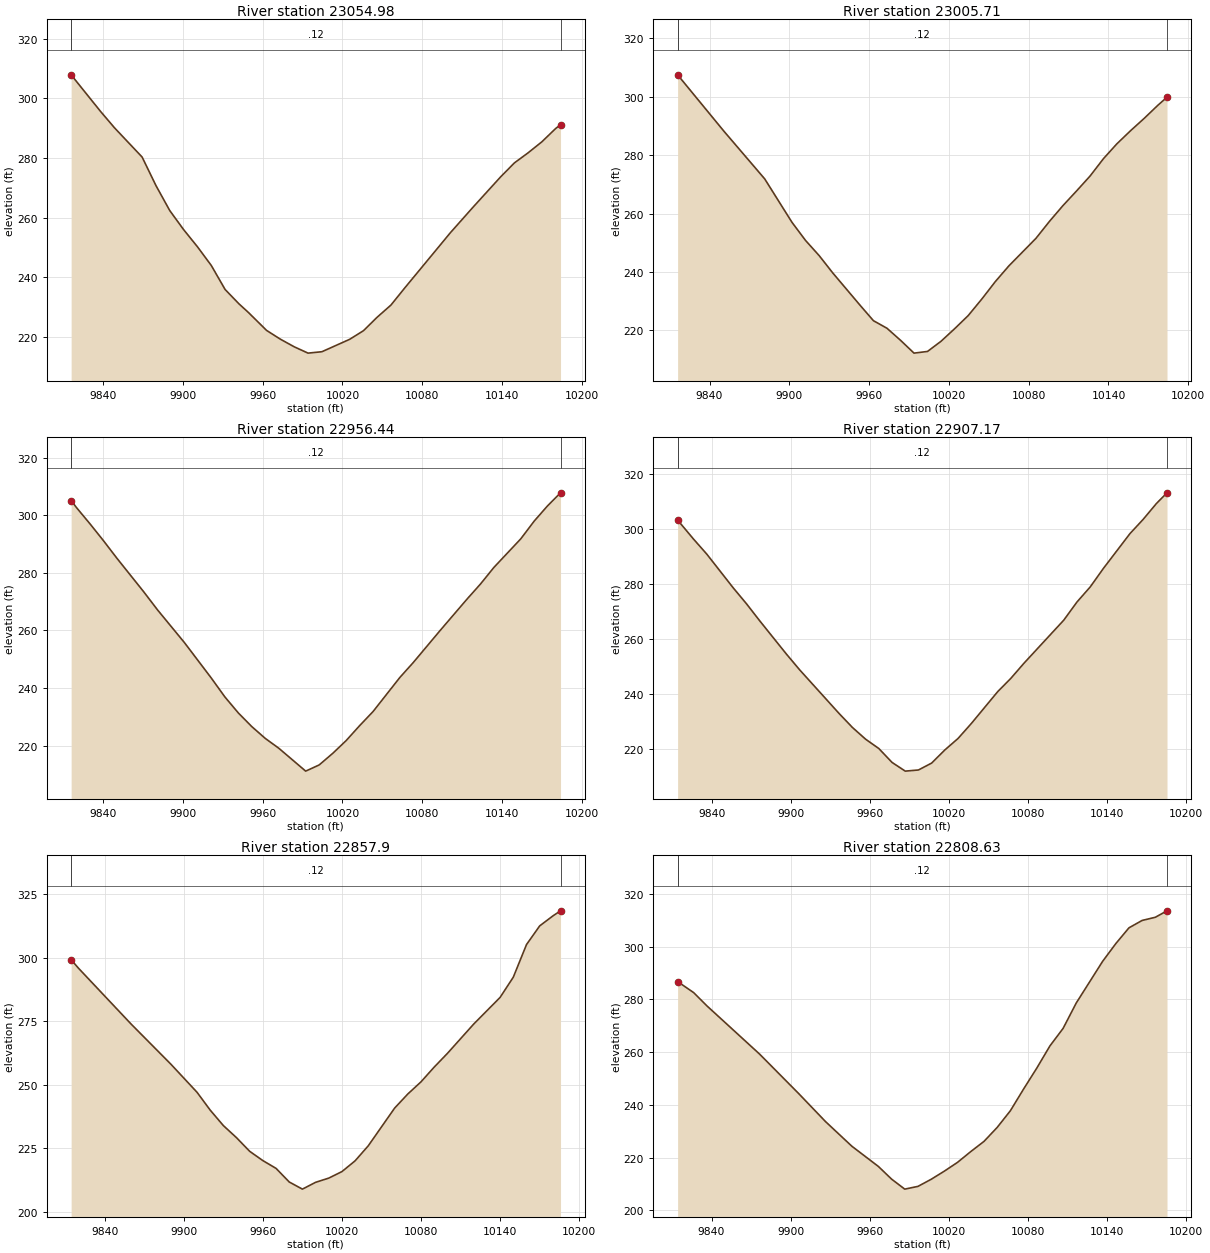
Type RM Length L Ch R = 1 ,23054.98,49.270500,49.270500,49.270500
XS GIS Cut Line= 5
443891.497091519736243.658117448 443841.42872203736419.666309637
 443840.76623302736421.553399543443832.131758486736450.745227739
443794.648355535736598.619852453
#Sta/Elev= 30
9816.009307.84679838.198295.56019848.594290.12169869.388280.31229879.784270.7785
9890.181 262.3959900.578256.02999910.975 250.2899921.371244.03969931.768235.9898
9942.165231.19199949.399228.24759962.958222.28249973.355219.33969983.752216.7932
9994.149214.674710004.59215.147810025.45219.299110035.83222.188110046.15226.7154
10056.46230.756810066.78236.452710101.17254.988410118.36263.608110138.99273.7081
10149.31278.361410159.63281.738710169.94285.415910180.26289.846210183.99291.1638
#Mann= 3 , 0 , 0
9816.009    0.12       09816.009    0.12       010183.99    0.12       0
#XS Ineff= 2 , 0
       0                               0
Bank Sta=9816.009,10183.99
Exp/Cntr=0.3,0.1

Type RM Length L Ch R = 1 ,23005.71,49.270500,49.270500,49.270500
XS GIS Cut Line= 5
443830.464774059736231.042077918443805.141504568736346.053506943
443792.989791212736410.139681262443792.640408763736412.108927794
443757.829887585 736591.76483228
#Sta/Elev= 30
9816.006307.53769850.777288.24519881.496271.87139901.975257.01119912.214250.7671
9922.454245.57239932.693239.62569953.056228.64549963.234223.27689973.412220.6847
9983.591216.56619993.769212.151210003.94212.731810014.13216.232110024.32220.5224
 10034.5225.010210044.69230.651710054.87236.643910065.06242.035610085.43251.4777
10095.62  257.31 10105.8262.730910115.99267.734310126.18272.868410136.36278.8816
 10146.3283.882810156.73288.442210166.92 292.64210177.11297.0946   10184299.8602
#Mann= 3 , 0 , 0
9816.006    0.12       09816.006    0.12       0   10184    0.12       0
#XS Ineff= 2 , 0
       0                               0
Bank Sta=9816.006,10184
Exp/Cntr=0.3,0.1

Type RM Length L Ch R = 1 ,22956.44,49.270500,49.270500,49.270500
XS GIS Cut Line= 5
443773.785079263736220.907782147443744.476921284736401.532559186
443744.127538835736403.501805719443741.020625488736422.150196864
443717.729156988 736584.58072888
#Sta/Elev= 30
9816.013305.06179820.159302.55439830.289296.9327 9840.42291.07339850.551284.9701
9870.813273.26129880.943267.12979901.205255.75439921.467243.41559931.597236.9123
9941.728231.33999951.859226.5966 9961.99222.4978 9972.12219.10369992.382211.1421
10002.52213.287210012.66217.287710022.78221.730510032.89226.903210042.99231.8002
10063.19243.6559 10073.3248.8549 10093.5259.9741 10113.7270.855910123.81276.0901
10133.91281.856910154.11291.775410164.22297.942710174.32303.2692   10184 307.746
#Mann= 3 , 0 , 0
9816.013    0.12       09816.013    0.12       0   10184    0.12       0
#XS Ineff= 2 , 0
       0                               0
Bank Sta=9816.013,10184
Exp/Cntr=0.3,0.1

Type RM Length L Ch R = 1 ,22907.17,49.270500,49.270500,49.270500
XS GIS Cut Line= 6
443712.669866344736212.979038515 443701.62356177 736310.26689482
443695.380726606736396.910345069443695.269786567736398.907265776
 443689.40023926736485.578539444443679.680103642736583.012231317
#Sta/Elev= 30
9814.219303.34739826.317296.40279836.381290.9178 9856.51278.58539866.574272.7827
9876.638266.55699896.767254.50969906.831248.75569936.929232.75179946.955227.7075
9956.981223.42189967.007220.02539977.033214.96319987.059211.78569997.085212.2045
10007.11214.722410017.13219.515510027.15223.700610037.18229.126210057.22240.7514
10067.24245.622210077.27251.174410107.39266.834410117.44273.461310127.49278.9554
10137.54285.735410157.64298.385610167.69303.595810177.74309.368910185.79313.2751
#Mann= 3 , 0 , 0
9814.219    0.12       09814.219    0.12       010185.79    0.12       0
#XS Ineff= 2 , 0
       0                               0
Bank Sta=9814.219,10185.79
Exp/Cntr=0.3,0.1

Type RM Length L Ch R = 1 , 22857.9,49.270500,49.270500,49.270500
XS GIS Cut Line= 6
443654.257974246736209.620697388443648.740098859736289.099043797
443646.186096627736394.177310062443646.075156588736396.174230768
443644.165544232736501.264813818443639.446312372736580.797164395
#Sta/Elev= 30
9814.221299.14579819.613295.9153 9859.71273.90379889.782258.19969909.796247.0866
9919.799 240.0719929.802233.99269939.805229.22579949.808223.87539959.811220.2321
9969.814217.17829979.817211.8282 9989.82209.03169999.824211.706410009.83213.3609
10019.83 215.92410029.83220.153210039.83226.061310059.84240.868410069.84246.4032
10079.84251.170710089.84256.947410099.84262.313910119.87273.8765 10139.9284.3421
10149.92292.291610159.94305.085810169.96312.431210179.97316.346810185.78318.3489
#Mann= 3 , 0 , 0
9814.221    0.12       09814.221    0.12       010185.78    0.12       0
#XS Ineff= 2 , 0
       0                               0
Bank Sta=9814.221,10185.78
Exp/Cntr=0.3,0.1

Type RM Length L Ch R = 1 ,22808.63,49.270500,49.270500,49.270500
XS GIS Cut Line= 6
443592.765036519736212.765069445443590.749825017736270.329842498
443591.475780112736318.535675354443600.532066742736439.680387932
443602.547560795736485.978708641443600.543178222736583.853710405
#Sta/Elev= 30
9814.228286.51179816.464285.9493 9826.47282.50579836.476277.50469876.498259.2118
9906.502244.07469926.519233.63949946.567224.27799966.616216.6501 9976.64  211.85
9986.664208.03489996.688209.072210006.72211.755710016.76 214.85910026.79218.2004
10036.83222.278310046.85226.133410056.86 231.43210066.87237.749410076.88245.9609
10086.89253.885410096.89262.323510106.89268.956910116.89278.602710136.89294.3687
10146.89301.0877 10156.9307.081110166.91 309.88610176.92 311.08610185.78313.5285
#Mann= 3 , 0 , 0
9814.228    0.12       09814.228    0.12       010185.78    0.12       0
#XS Ineff= 2 , 0
       0                               0
Bank Sta=9814.228,10185.78
Exp/Cntr=0.3,0.1

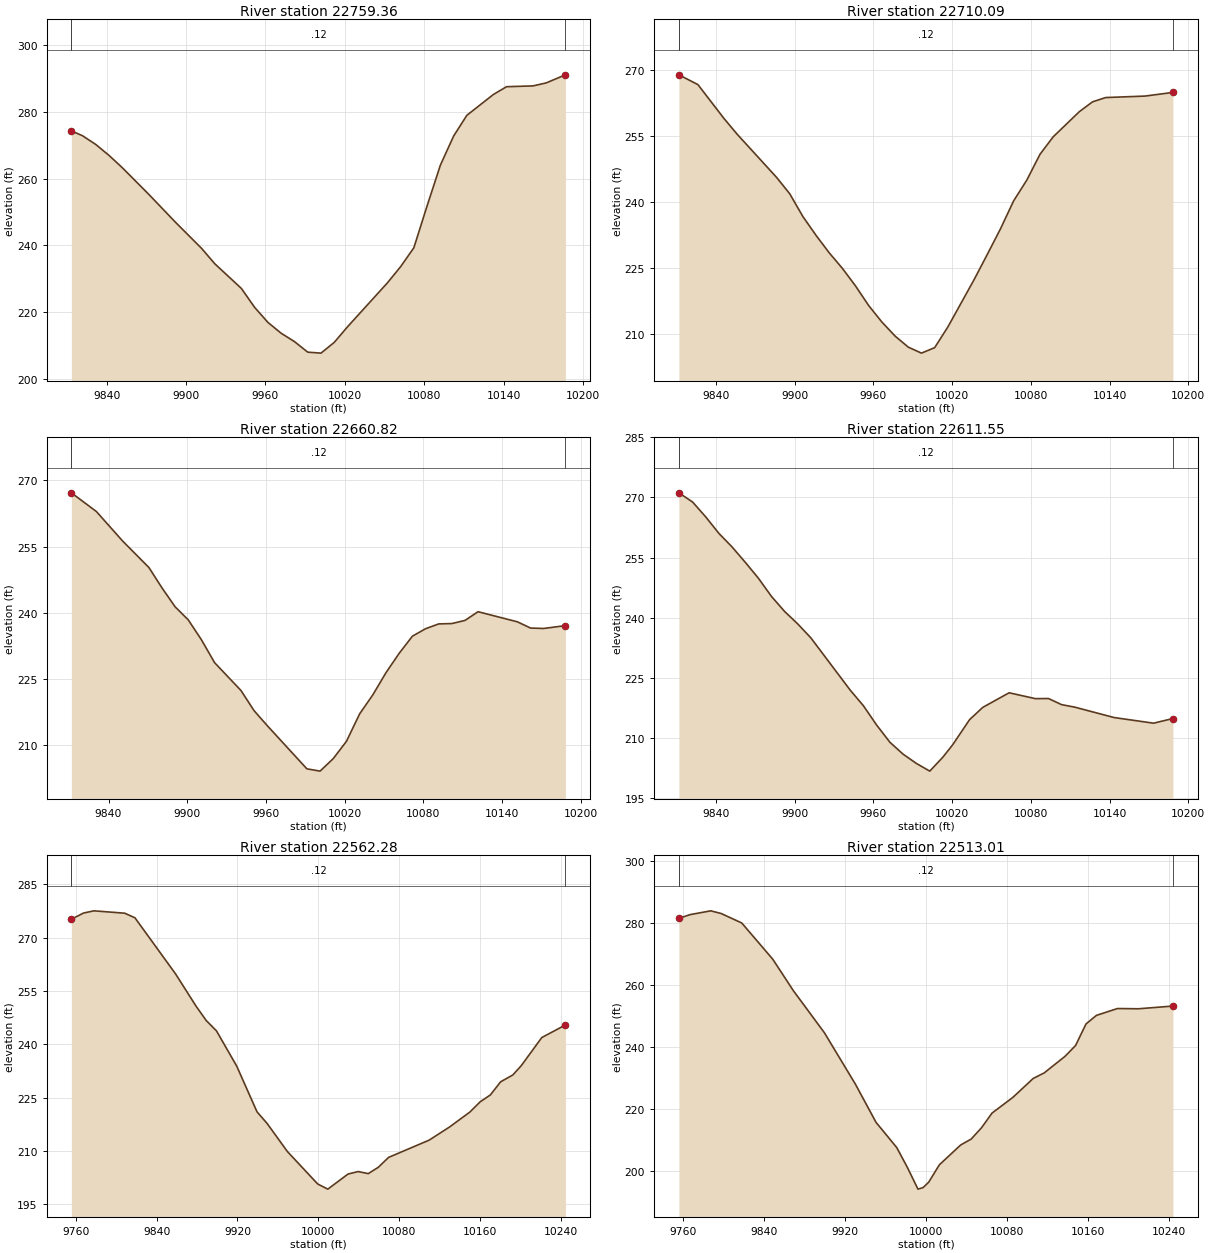
Type RM Length L Ch R = 1 ,22759.36,49.270500,49.270500,49.270500
XS GIS Cut Line= 6
443539.513460349736216.586561629 443538.60419815736262.483503873
443540.383007199736315.484058848443555.532449337736499.239267001
443556.377195215736542.674108393 443555.16713206736589.495729261
#Sta/Elev= 30
9813.199274.26679821.614272.81779831.616270.20919841.618266.9434 9851.62263.2786
9871.628255.30869891.639247.02359911.651239.08459921.687234.45639941.762227.0817
  9951.8221.40389961.838 216.9039971.876213.65399981.914211.16069991.951207.9933
10001.99207.701310012.02 210.92710022.05215.595410052.14228.721210062.17 233.584
 10072.2239.258110082.23251.822310092.26264.001610102.28272.709610112.28278.9309
10132.28285.148910142.29287.500510162.29287.7383 10172.3 288.639 10186.8291.0577
#Mann= 3 , 0 , 0
9813.199    0.12       09813.199    0.12       0 10186.8    0.12       0
#XS Ineff= 2 , 0
       0                               0
Bank Sta=9813.199,10186.8
Exp/Cntr=0.3,0.1

Type RM Length L Ch R = 1 ,22710.09,49.270500,49.270500,49.270500
XS GIS Cut Line= 6
443489.078896069736220.494330618443488.207734788736267.918740077
443489.877214491736312.231995524443507.378274928736503.978879785
443508.552887021 736546.34180262443507.406430531736596.276509984
#Sta/Elev= 30
9811.673268.99269826.181266.76769846.185258.99269856.186255.42639886.206245.5931
9896.213241.86169906.231236.67569916.276232.38339926.321228.40219936.366224.8529
9946.411220.83499956.456216.35579966.501212.61149976.546209.42029986.592206.9001
9996.637205.539110006.68206.786110016.72211.495510036.79222.318610046.83228.0578
10056.87233.882710066.91240.265710076.95245.001510086.98250.866510097.02254.8533
10117.03260.602610127.03262.833110137.03263.808810167.04264.148910188.32 264.977
#Mann= 3 , 0 , 0
9811.673    0.12       09811.673    0.12       010188.32    0.12       0
#XS Ineff= 2 , 0
       0                               0
Bank Sta=9811.673,10188.32
Exp/Cntr=0.3,0.1

Type RM Length L Ch R = 1 ,22660.82,49.270400,49.270400,49.270400
XS GIS Cut Line= 6
443441.140372934736225.933876603443439.261044091736273.328253401
443440.816629956736326.330401798443458.920532484736507.566300742
443459.799417355736548.146963328443457.929575817 736601.55618913
#Sta/Elev= 30
9811.683267.15739830.765262.9287 9850.78256.24839870.792250.26439880.796245.6445
  9890.8241.36649900.805238.41559910.809233.93649920.858 228.7439940.969222.4426
9951.025217.8599 9961.08214.47089991.247204.7142 10001.3204.194910011.37207.0351
10021.43210.949410031.49217.162110041.56221.470610051.61226.497110061.64230.8606
10071.67234.7177 10081.7236.407110091.72237.497810101.73237.581310111.74238.2848
10121.74240.263210151.75237.972910161.76236.563310171.76236.471710188.33237.1107
#Mann= 3 , 0 , 0
9811.683    0.12       09811.683    0.12       010188.33    0.12       0
#XS Ineff= 2 , 0
       0                               0
Bank Sta=9811.683,10188.33
Exp/Cntr=0.3,0.1

Type RM Length L Ch R = 1 ,22611.55,49.270500,49.270500,49.270500
XS GIS Cut Line= 6
443397.135212653736234.575920332443392.083036274736334.852071786
443395.425360653736384.751183229443409.515799769736486.738431224
443410.084589437736544.126627533443405.622425728736609.691529909
#Sta/Elev= 30
9811.702271.14429822.163268.8492  9832.2265.12699842.236261.00759852.272 257.629
9862.297253.80749872.299249.83829882.301  245.289892.303241.53199902.305238.4194
9912.307 234.9429942.374221.86539952.397217.99129962.422213.18989972.553208.8875
9982.685205.88999992.817203.583610002.96201.673810013.11 205.22510020.41208.2506
10033.32214.530710043.37217.590310063.45221.232910083.46219.766510093.46219.7979
10103.46218.269810113.46217.645410143.51215.048910173.58213.6406 10188.3214.8084
#Mann= 3 , 0 , 0
9811.702    0.12       09811.702    0.12       0 10188.3    0.12       0
#XS Ineff= 2 , 0
       0                               0
Bank Sta=9811.702,10188.3
Exp/Cntr=0.3,0.1

Type RM Length L Ch R = 1 ,22562.28,49.270500,49.270500,49.270500
XS GIS Cut Line= 6
443377.564297953736183.089909732443364.622122027 736255.97419077
443356.072540841736329.196594307443351.820200383736474.265104006
443347.327030808736533.771767869 443325.36291474736667.940960111
#Sta/Elev= 30
9755.705275.21739767.801276.95819777.958277.57799808.427276.91159818.584275.6207
9858.952259.76269879.088250.74129889.156246.70119899.224243.81949919.281233.8892
9939.317221.05069949.335217.77089969.345209.89019999.346200.754610009.35199.3123
10029.35 203.55910039.35204.251910049.36203.673910059.38 205.47810069.41208.2304
10109.53213.085610129.71216.780810149.89221.002910159.98223.855710170.07225.7965
10180.25229.496110192.24231.4047 10200.6234.013510220.95 241.943 10244.3245.4681
#Mann= 3 , 0 , 0
9755.705    0.12       09755.705    0.12       0 10244.3    0.12       0
#XS Ineff= 2 , 0
       0                               0
Bank Sta=9755.705,10244.3
Exp/Cntr=0.3,0.1

Type RM Length L Ch R = 1 ,22513.01,49.270500,49.270500,49.270500
XS GIS Cut Line= 6
443356.886290741736184.116301472443313.644809826736392.529242367
  443304.4572077736421.510561241  443293.0241957736454.624256473
443257.901739855736590.781337835443239.050766718736657.815026811
#Sta/Elev= 30
9755.746281.58259766.861282.78779787.287284.0133  9797.5 283.1579817.926280.0857
9848.565268.38819868.991258.1972 9899.63244.63489930.269228.03429950.695215.6798
9971.189207.5238 9981.68201.1296 9992.17194.09199997.204194.590610002.76196.3101
10013.32201.945610034.43208.360910044.76210.255610055.08213.944110065.41218.6582
10086.07223.7487 10106.2229.868410117.05231.6525 10137.7237.024410148.03240.4982
10158.36247.463610168.68 250.23310189.43252.4433 10210.2252.365910244.29253.2435
#Mann= 3 , 0 , 0
9755.746    0.12       09755.746    0.12       010244.29    0.12       0
#XS Ineff= 2 , 0
       0                               0
Bank Sta=9755.746,10244.29
Exp/Cntr=0.3,0.1

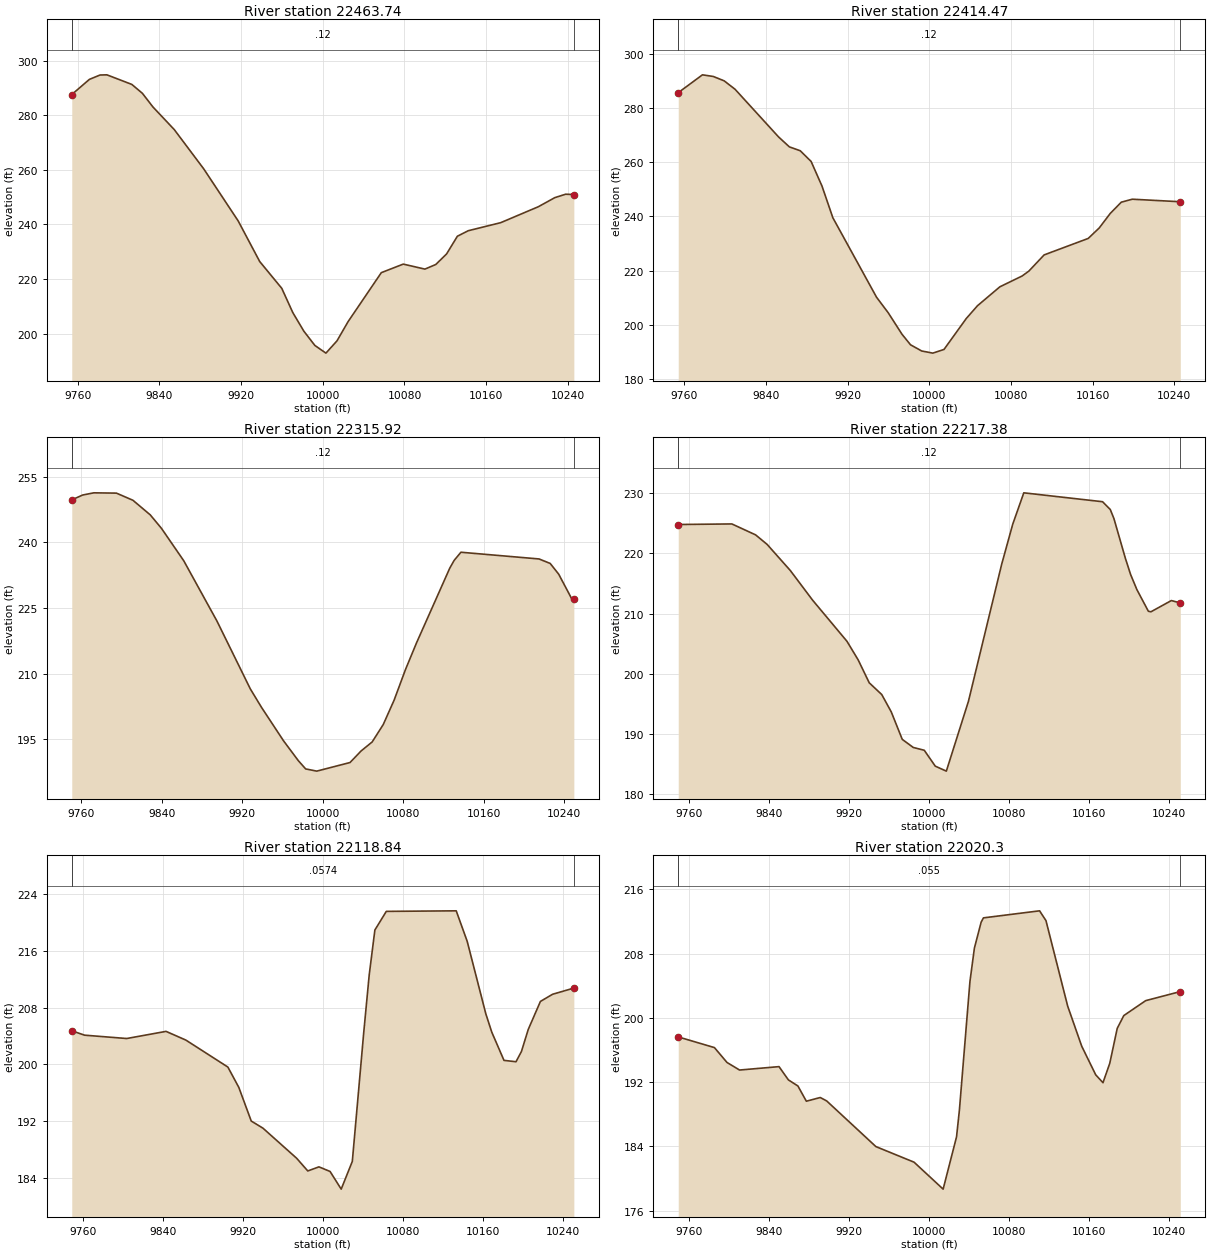
Type RM Length L Ch R = 1 ,22463.74,49.270500,49.270500,49.270500
XS GIS Cut Line= 6
443334.283882035736168.359900091443299.375486027736292.841841015
443284.232141683736340.862898377443259.542882303736401.255081161
443232.089773102736466.453598581443173.403901102736632.543928504
#Sta/Elev= 30
 9754.12287.67679771.402293.23989781.788294.83759788.503294.90769812.945291.3902
9823.331288.10919833.716283.08019854.488274.82639883.404260.38779917.123241.3083
9938.226226.40219959.832216.57169970.636207.67319981.439200.86319992.242 195.619
10003.08192.807110013.93197.323510024.78204.362510057.32222.330310078.81225.4652
10100.02223.634610110.63225.313710121.23229.183410131.84235.695710142.44237.7086
10174.26240.668110211.09246.509910227.29 249.855 10237.9251.1108 10245.9250.9841
#Mann= 3 , 0 , 0
 9754.12    0.12       0 9754.12    0.12       0 10245.9    0.12       0
#XS Ineff= 2 , 0
       0                               0
Bank Sta=9754.12,10245.9
Exp/Cntr=0.3,0.1

Type RM Length L Ch R = 1 ,22414.47,98.541000,98.541000,98.541000
XS GIS Cut Line= 6
443303.260912975736152.722313866443246.371793592 736308.59216403
443214.676275247736380.918091104443213.836720234736382.733345186
443180.018789601736458.751103374443119.129770767736608.557169829
#Sta/Elev= 30
9754.107285.68029777.822292.27229788.467291.66359799.112  290.059809.758286.9486
9852.339269.36699862.984265.67259873.629264.24549884.274260.29719894.919251.2147
9905.565239.51719948.366210.17679959.784204.4507 9973.28196.5241 9981.62192.6284
9992.539190.338410003.48189.542610014.43190.900810036.32202.353310047.26 207.045
10069.15214.018810090.95218.014710097.53219.812810112.53225.798710155.71231.8805
10166.51235.7527 10177.3241.1134 10188.1245.260110198.89246.360310245.91245.4246
#Mann= 3 , 0 , 0
9754.107    0.12       09754.107    0.12       010245.91    0.12       0
#XS Ineff= 2 , 0
       0                               0
Bank Sta=9754.107,10245.91
Exp/Cntr=0.3,0.1

Type RM Length L Ch R = 1 ,22315.92,98.541000,98.541000,98.541000
XS GIS Cut Line= 6
443232.385524043736115.360991171443189.781599396736199.842799447
443125.237809889736339.552800858443124.398254876 736341.36805494
443069.918464572736458.880672957443018.511773894736566.202768312
#Sta/Elev= 30
9750.485249.6915 9761.28250.8048 9772.48251.30869794.879251.23889811.304249.6042
9828.478246.27539839.678243.17779861.798235.78389894.845221.98149927.891206.5309
9938.907202.34279960.938  194.659975.723190.08679982.969188.21499993.985187.7096
10027.05189.673310038.07192.318110049.09194.381210060.12198.3704 10070.9203.9339
10082.16210.905110093.18217.029410126.25234.119210130.53 235.85510137.31237.7306
10214.93236.195910226.02235.174810234.51232.707210248.19226.765810249.53227.0746
#Mann= 3 , 0 , 0
9750.485    0.12       09750.485    0.12       010249.53    0.12       0
#XS Ineff= 2 , 0
       0                               0
Bank Sta=9750.485,10249.53
Exp/Cntr=0.3,0.1

Type RM Length L Ch R = 1 ,22217.38,98.540900,98.540900,98.540900
XS GIS Cut Line= 6
443157.730375013736081.135083126443120.954591594736133.351294582
443085.389545833736194.305678269442988.593337823736397.945557647
442955.585436552736460.770999117 442920.55550939736522.815013619
#Sta/Elev= 30
 9748.94224.78019802.592224.87279826.293223.06149837.871221.47239861.027217.1448
9883.378212.21169917.712205.38919928.883202.31259939.981198.50259952.485196.5525
9961.989193.67869972.994189.11559983.998187.76999995.002187.306510006.03184.6648
10017.09183.841710039.22195.448210072.42218.174610083.48224.822410094.55230.0376
10173.32228.560610181.03227.273510184.69225.767410196.18219.153910201.37216.4822
10207.66213.974310219.15210.375910221.71210.290610242.11212.153710251.09211.7649
#Mann= 3 , 0 , 0
 9748.94    0.12       0 9748.94    0.12       010251.09    0.12       0
#XS Ineff= 2 , 0
       0                               0
Bank Sta=9748.94,10251.09
Exp/Cntr=0.3,0.1

Type RM Length L Ch R = 1 ,22118.84,98.541000,98.541000,98.541000
XS GIS Cut Line= 6
443091.074218758736056.024499126443035.102117426736114.249796854
442996.436879605736165.427743102 442969.97925658736209.210579321
442900.518671025736344.159301375442814.982688464736472.406805451
#Sta/Elev= 30
9748.966 204.7369761.753204.11569803.908203.64369843.243204.65259863.117 203.418
9905.095199.61299916.025196.74549928.464191.99349940.148190.99249973.846186.7451
9985.005184.95149996.165185.529610007.29184.878110018.42182.386210029.54186.3001
10040.87204.354210046.43212.6177 10052.1218.959210063.54221.588310133.44221.6663
10144.43217.359910163.06207.124510168.99204.549710181.21200.558910193.25200.3653
10198.67201.812810205.45204.909910217.65208.878110229.84209.890910251.08  210.76
#Mann= 3 , 0 , 0
9748.966  0.0574       09748.966  0.0574       010251.08  0.0574       0
#XS Ineff= 2 , 0
       0                               0
Bank Sta=9748.966,10251.08
Exp/Cntr=0.3,0.1

Type RM Length L Ch R = 1 , 22020.3,98.541000,98.541000,98.541000
XS GIS Cut Line= 6
443053.824709815736039.489287073443002.973241971 736078.14110092
442967.903857787736108.378195635442891.412596439736182.347426307
442826.630332362736239.495893903442684.736035332736379.285637389
#Sta/Elev= 30
9748.927197.63399785.134196.30399797.694194.45439810.255193.51119849.736193.9352
9859.106192.28399868.632 191.5289877.056189.63099890.967190.09169897.402189.6663
9946.611 183.985  9984.8182.043510013.87178.691510027.28185.194910030.14188.5124
10040.68204.515210045.15208.6883 10051.9211.912310054.19212.446510110.34 213.323
10116.74212.100310138.42201.474110152.45 196.48710166.49192.914910173.74191.9342
10180.53194.344810187.99198.692310194.57200.289210216.48202.147610251.09203.2748
#Mann= 3 , 0 , 0
9748.927   0.055       09748.927   0.055       010251.09   0.055       0
#XS Ineff= 2 , 0
       0                               0
Bank Sta=9748.927,10251.09
Exp/Cntr=0.3,0.1

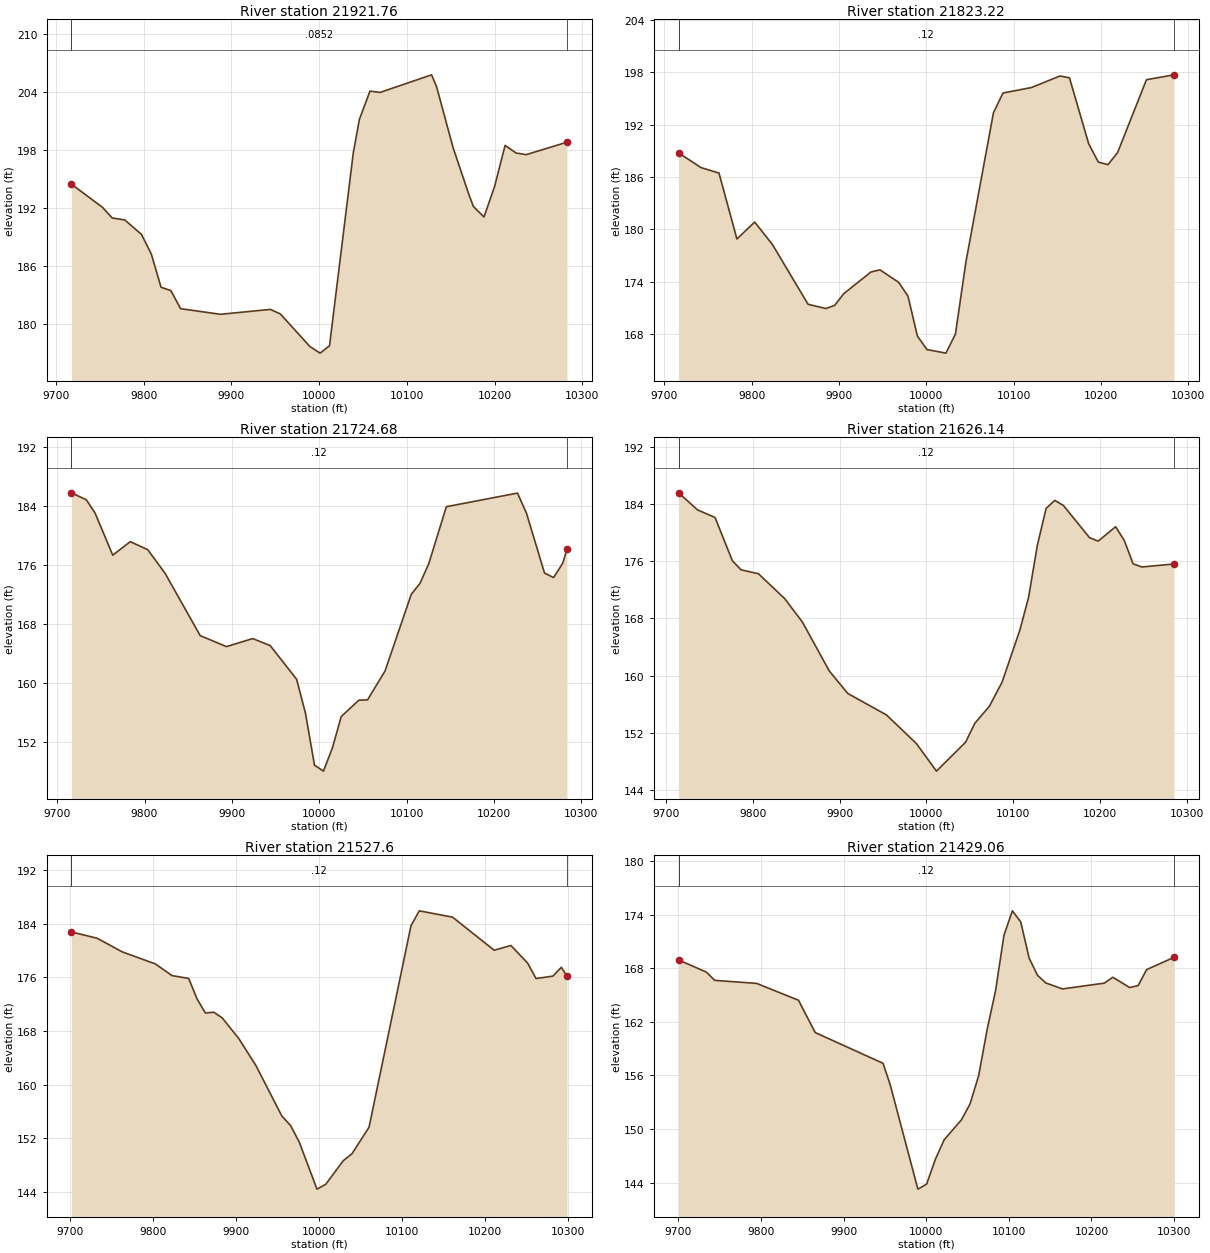
Type RM Length L Ch R = 1 ,21921.76,98.541000,98.541000,98.541000
XS GIS Cut Line= 6
443056.691462985735998.156285942442942.205595098736054.473792634
442829.064842971736115.880554042442772.513592672736144.030007307
442679.970997443736201.234795349442566.445662022736277.281156235
#Sta/Elev= 30
9717.524 194.4779752.842192.09699763.987190.99049778.339190.7889 9797.42 189.292
9808.564187.27429819.709183.83729830.853183.49659841.998181.62819887.444181.0474
9944.334181.55539955.712181.08419989.464177.7196   10001 177.04110011.76177.7974
10038.86197.703510045.85201.167310057.88204.086210069.36203.948910128.15205.7658
10133.96204.501910152.58198.267910170.55 193.43610175.87192.171110187.91191.0928
10199.94194.234110211.98 198.48310224.45197.696510236.05197.527910282.46198.8126
#Mann= 3 , 0 , 0
9717.524  0.0852       09717.524  0.0852       010282.46  0.0852       0
#XS Ineff= 2 , 0
       0                               0
Bank Sta=9717.524,10282.46
Exp/Cntr=0.3,0.1

Type RM Length L Ch R = 1 ,21823.22,98.540900,98.540900,98.540900
XS GIS Cut Line= 6
443039.863188366735966.601624504442984.282703677735981.083477088
442856.931739813736005.938366574442812.142916074736018.436951544
442612.213248624736103.007275769442506.398426577736152.186012748
#Sta/Elev= 30
 9716.28188.77329741.974187.08419762.641186.44889783.174178.88389803.552180.8266
9823.929 178.2329864.684171.38549885.061170.8963 9895.25171.26939905.476172.5975
9936.622175.08849947.004175.33949968.345173.91289979.064172.3275 9989.89167.7378
10000.79166.186310022.56165.776810033.44167.9655 10045.4176.216210076.97193.3703
10087.86195.639710120.51196.268710153.16197.596610164.04197.383910186.05189.8139
10197.08187.713510208.11187.415110219.13188.794910252.22  197.1710283.76197.7292
#Mann= 3 , 0 , 0
 9716.28    0.12       0 9716.28    0.12       010283.76    0.12       0
#XS Ineff= 2 , 0
       0                               0
Bank Sta=9716.28,10283.76
Exp/Cntr=0.3,0.1

Type RM Length L Ch R = 1 ,21724.68,98.541000,98.541000,98.541000
XS GIS Cut Line= 6
443021.812399174 735950.49242583442879.569678934735959.896874289
442700.216872232735938.009104795442642.056127433735936.690745301
442556.418557139735946.688869738442460.286640842735970.468454316
#Sta/Elev= 30
9716.289185.73779733.311184.79999743.435  182.989763.576177.3031 9783.65179.1294
9803.689178.04259823.689174.82069863.701166.41829893.774164.92789923.847166.0122
9943.895165.0646 9974.12160.51659984.314155.90499994.611148.884610004.86148.0785
10015.11151.218410025.25155.468110045.39157.674210055.39157.7206 10075.4161.6303
10105.43172.004510115.46 173.48710125.49176.1571 10145.6183.858510227.05185.7021
10237.29183.007210258.02174.880410268.41174.270810278.79176.190210283.69178.0863
#Mann= 3 , 0 , 0
9716.289    0.12       09716.289    0.12       010283.69    0.12       0
#XS Ineff= 2 , 0
       0                               0
Bank Sta=9716.289,10283.69
Exp/Cntr=0.3,0.1

Type RM Length L Ch R = 1 ,21626.14,98.541000,98.541000,98.541000
XS GIS Cut Line= 6
443046.925186823735914.893432103442967.306163422735919.054550747
442890.675899743735907.444224308442676.994185551735815.070048772
442600.544369642 735810.85072095442498.558669552735824.571586414
#Sta/Elev= 30
9714.423185.55489736.469183.16659756.549182.1111 9776.55 176.053 9786.55174.7979
9806.603174.24629836.841  170.779857.247167.4964 9888.33160.64369909.556157.5182
9954.175154.51529988.629150.520610011.78146.666710045.37150.711310056.02153.3572
10072.66 155.71310087.41159.100110107.92166.375510117.99170.968610128.05178.2115
10138.12183.369610148.13184.496410158.13183.783810188.16179.2975 10198.2178.8083
10218.29180.816610228.33178.876910238.41175.636510248.57175.195810285.58175.6086
#Mann= 3 , 0 , 0
9714.423    0.12       09714.423    0.12       010285.58    0.12       0
#XS Ineff= 2 , 0
       0                               0
Bank Sta=9714.423,10285.58
Exp/Cntr=0.3,0.1

Type RM Length L Ch R = 1 , 21527.6,98.541000,98.541000,98.541000
XS GIS Cut Line= 6
443125.618701299735802.032710645443048.383931059735809.941246448
442952.982418615735805.027453577442793.182499052735759.983607603
442721.545160883735749.496370837442538.347194264735763.695508733
#Sta/Elev= 30
9701.791182.77669732.725181.83519762.812179.8096 9802.86178.00099822.862176.2631
9842.908175.83599852.959 172.793 9863.01170.68119873.061   170.89883.193169.9611
9903.498166.82789923.935162.81979955.043155.31579965.614153.88399976.185151.3724
9997.327144.405610007.87145.127810028.99148.650710039.55149.7004   10060153.6427
10110.46183.696910120.49185.9268 10160.5184.9855 10210.6180.050410230.72180.7574
10250.85178.1369   10261175.827210281.29176.188610291.44177.498610298.19176.1918
#Mann= 3 , 0 , 0
9701.791    0.12       09701.791    0.12       010298.19    0.12       0
#XS Ineff= 2 , 0
       0                               0
Bank Sta=9701.791,10298.19
Exp/Cntr=0.3,0.1

Type RM Length L Ch R = 1 ,21429.06,98.540900,98.540900,98.540900
XS GIS Cut Line= 6
443108.247276932735616.941382818442924.619185328735647.604515071
 442862.42635909735663.047496555442752.308715727735699.086515117
  442606.2355058735723.425776588442522.517369003735741.065366474
#Sta/Elev= 30
9700.089 168.9369733.796167.57549743.935166.64939794.627166.31179845.319164.4241
9865.596160.80529947.689157.36469956.404 154.9519989.873143.279110000.46143.8438
10011.08146.6273 10021.7148.801910042.69 151.04710053.07152.824310063.46155.9911
 10073.7161.137910083.89165.484610094.08 171.70310104.26174.4338 10114.4173.1908
10124.52169.152310134.64167.221410144.76166.3572   10165165.692510215.62166.3409
10225.84166.998610246.28165.8466 10256.5166.066610266.72167.849510299.92169.2279
#Mann= 3 , 0 , 0
9700.089    0.12       09700.089    0.12       010299.92    0.12       0
#XS Ineff= 2 , 0
       0                               0
Bank Sta=9700.089,10299.92
Exp/Cntr=0.3,0.1

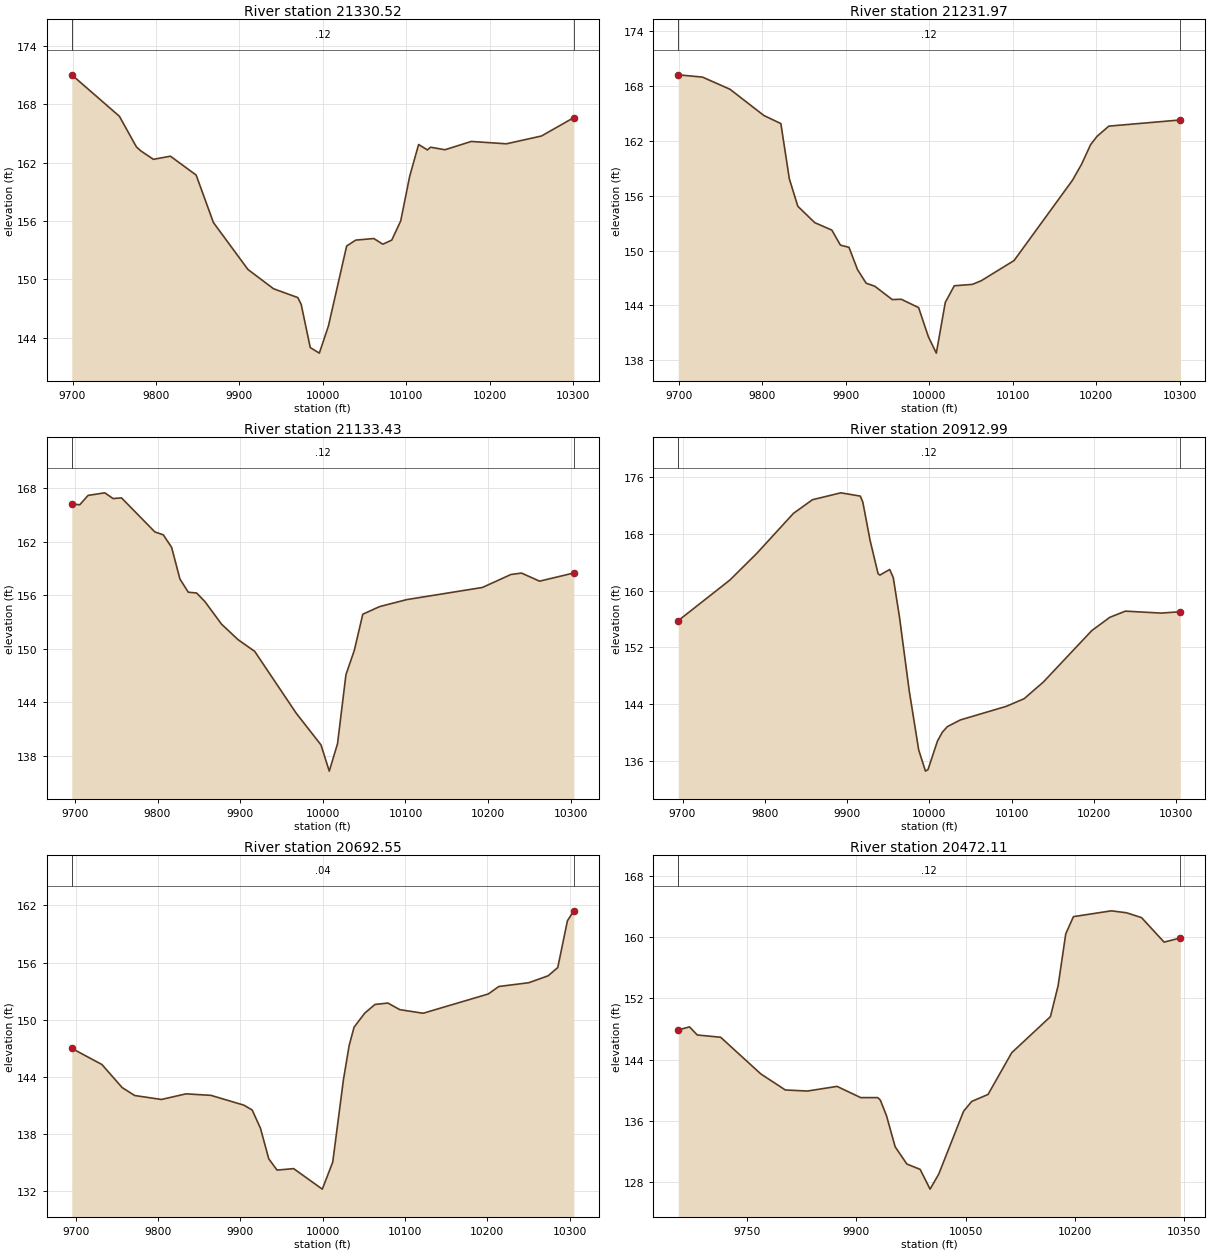
Type RM Length L Ch R = 1 ,21330.52,98.541000,98.541000,98.541000
XS GIS Cut Line= 6
 443071.05289243735509.047948491442942.818280964  735534.2091207
442863.181596743735555.344847411442812.899754058735573.225946862
442673.460851931735631.087643534442498.118463358735688.345022433
#Sta/Elev= 30
9699.069171.02629756.191166.76139776.573163.6109 9781.92163.19699796.954162.3322
9817.335162.65579848.184160.71469868.877155.83229910.262151.00179940.959149.0208
9970.029148.11129974.099147.41639984.971142.97159995.844142.396810006.76145.1868
10028.59153.4171 10039.5154.023810061.22154.184910071.95153.602510082.68154.0248
 10093.4155.993210104.13160.576410114.86163.858810125.41163.299110129.11163.5815
10146.45163.3188   10178164.172510220.08163.930110262.16164.733210300.96166.6251
#Mann= 3 , 0 , 0
9699.069    0.12       09699.069    0.12       010300.96    0.12       0
#XS Ineff= 2 , 0
       0                               0
Bank Sta=9699.069,10300.96
Exp/Cntr=0.3,0.1

Type RM Length L Ch R = 1 ,21231.97,98.541000,98.541000,98.541000
XS GIS Cut Line= 6
443036.024167436735429.742668489442865.757662381735461.009349865
442819.139819876735471.919880997442775.501243007735484.711514796
442686.948110321735518.349730021442466.514919388735615.050408499
#Sta/Elev= 30
9699.043169.18689728.151 168.9379761.087167.61149801.756164.74289822.091163.8614
9832.258157.82469842.425154.8326 9862.76153.04149883.205152.23149893.475150.5893
9903.745150.34889914.015147.91079924.348146.43069934.769146.0973 9955.61144.6439
9966.389144.67959987.208143.7679    9999 140.56910008.45138.794810019.22144.3354
   10030146.153110051.58146.299610062.39146.704810101.71 148.90910171.59157.6607
10182.51159.406110193.43161.563610201.28162.482110215.27163.583610300.97164.2577
#Mann= 3 , 0 , 0
9699.043    0.12       09699.043    0.12       010300.97    0.12       0
#XS Ineff= 2 , 0
       0                               0
Bank Sta=9699.043,10300.97
Exp/Cntr=0.3,0.1

Type RM Length L Ch R = 1 ,21133.43,220.440000,220.440000,220.440000
XS GIS Cut Line= 6
443014.558334118735369.925907218442868.463982577735391.036638848
442694.612879256735403.465865202442658.562766713735410.379053155
442592.197853916735438.569074792442439.021648442735526.512979672
#Sta/Elev= 30
9696.211166.23219705.868166.14379715.972167.1953 9736.18167.48329746.284166.8387
9756.388166.91789796.803163.09449806.907162.77569817.011161.37399827.115157.8086
9837.219156.3358  9847.3156.24369857.339 155.2829877.418152.75419897.497151.0093
9917.575149.69789967.754 142.7689997.777139.208210007.78136.264810017.79139.3429
10027.96147.081410038.15149.827510048.33153.862510068.73154.722510101.74155.5094
10193.06156.865810227.65158.324110240.44158.480610262.24157.574210303.73158.4909
#Mann= 3 , 0 , 0
9696.211    0.12       09696.211    0.12       010303.73    0.12       0
#XS Ineff= 2 , 0
       0                               0
Bank Sta=9696.211,10303.73
Exp/Cntr=0.3,0.1

Type RM Length L Ch R = 1 ,20912.99,220.440000,220.440000,220.440000
XS GIS Cut Line= 6
442974.166566625735048.530264623442848.450249321735100.064547646
442686.355729161735197.115625742442659.028955622735276.664636084
442636.332103122735315.074532411442523.030509107735419.300911165
#Sta/Elev= 30
9694.794155.75689757.637161.49229790.247165.24439834.792170.88639857.818172.8092
9892.356 173.7879916.099173.32439919.151172.46169927.989167.06749937.637162.3904
9939.879162.18519951.769162.97179956.122161.83859963.659156.28919975.549145.8427
9987.049137.51939995.287134.53329998.346134.749910009.82138.768210015.68140.0029
10021.83140.808410037.68141.7545 10093.7  143.6810115.19  144.75 10138.5147.0963
10197.38154.353310219.31156.227310238.25157.099810281.75156.823810304.98157.0165
#Mann= 3 , 0 , 0
9694.794    0.12       09694.794    0.12       010304.98    0.12       0
#XS Ineff= 2 , 0
       0                               0
Bank Sta=9694.794,10304.98
Exp/Cntr=0.3,0.1

Type RM Length L Ch R = 1 ,20692.55,220.440000,220.440000,220.440000
XS GIS Cut Line= 6
442654.560201541734965.601497133442611.136930223735001.016446956
442579.637961809735060.756186207442576.428226741735221.252088532
442468.142864078735344.171079252442338.352676321735436.026049023
#Sta/Elev= 30
9694.985146.99389731.632145.29789756.195142.87889771.412142.04279803.937141.6276
9833.801 142.2179864.068142.06049904.113141.03219914.201140.52279924.289138.6149
9934.377135.39829944.465134.21339964.626134.36859999.442132.214710012.13135.0462
 10025.1143.680110032.09147.285310038.07149.217410051.04150.691610063.49151.6042
 10079.2151.749510093.66151.056410122.01150.679410201.12152.700910213.92153.4858
10250.39153.884710273.87  154.6110285.61155.474910297.35160.387210305.15161.4318
#Mann= 3 , 0 , 0
9694.985    0.04       09694.985    0.04       010305.15    0.04       0
#XS Ineff= 2 , 0
       0                               0
Bank Sta=9694.985,10305.15
Exp/Cntr=0.3,0.1

Type RM Length L Ch R = 1 ,20472.11,220.440000,220.440000,220.440000
XS GIS Cut Line= 6
442709.511342233734931.535719992442582.252580859 734985.93143365
442384.689085003735105.171680886442331.795328794735131.697469659
442218.509134531735172.334505945442083.438435123735208.162201638
#Sta/Elev= 30
9655.621147.87599671.106148.26769681.776147.20829713.788146.91389768.876142.1203
9802.517140.01799832.874139.87769873.456140.4869 9905.95139.01799929.302139.0181
9932.861138.69339941.269136.67289953.236132.57949969.272130.33139987.478129.6344
10001.11127.0492 10012.9128.993510047.08137.235810058.27138.522410080.64139.4329
10113.05144.8836 10166.2149.609110176.73153.640510187.26 160.44710197.79 162.688
10249.88163.4474 10270.6 163.19110291.22162.559810322.15159.354810344.39159.8981
#Mann= 3 , 0 , 0
9655.621    0.12       09655.621    0.12       010344.39    0.12       0
#XS Ineff= 2 , 0
       0                               0
Bank Sta=9655.621,10344.39
Exp/Cntr=0.3,0.1