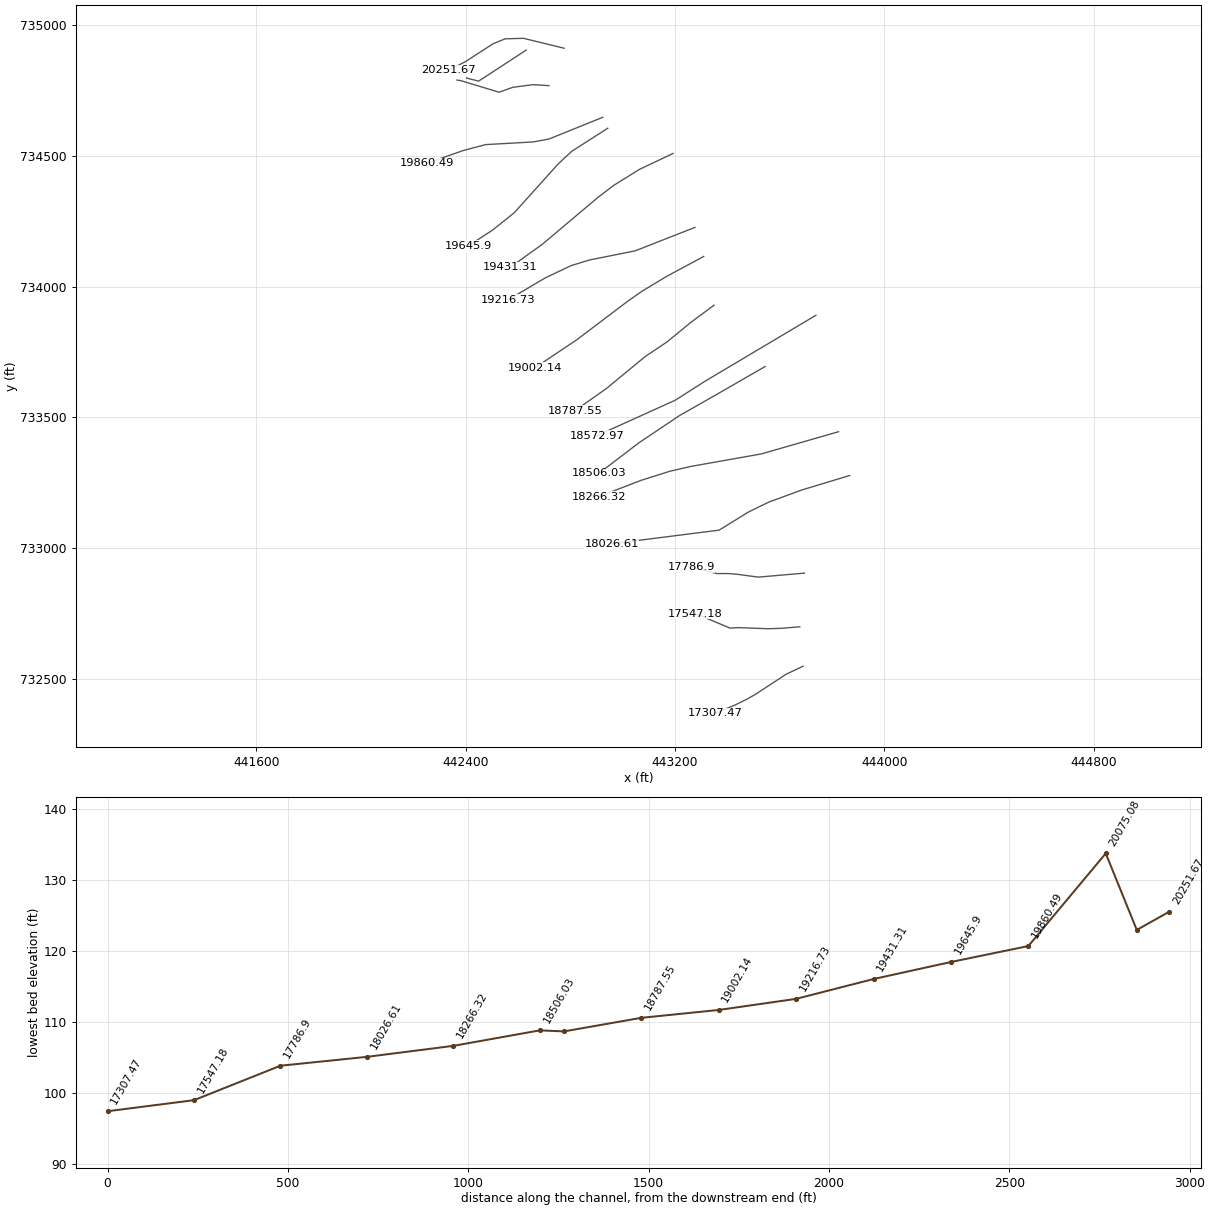
HEC-RAS study 708_ras.prj: 708

--- 708_ras.g01 (geometry) --- (continued)

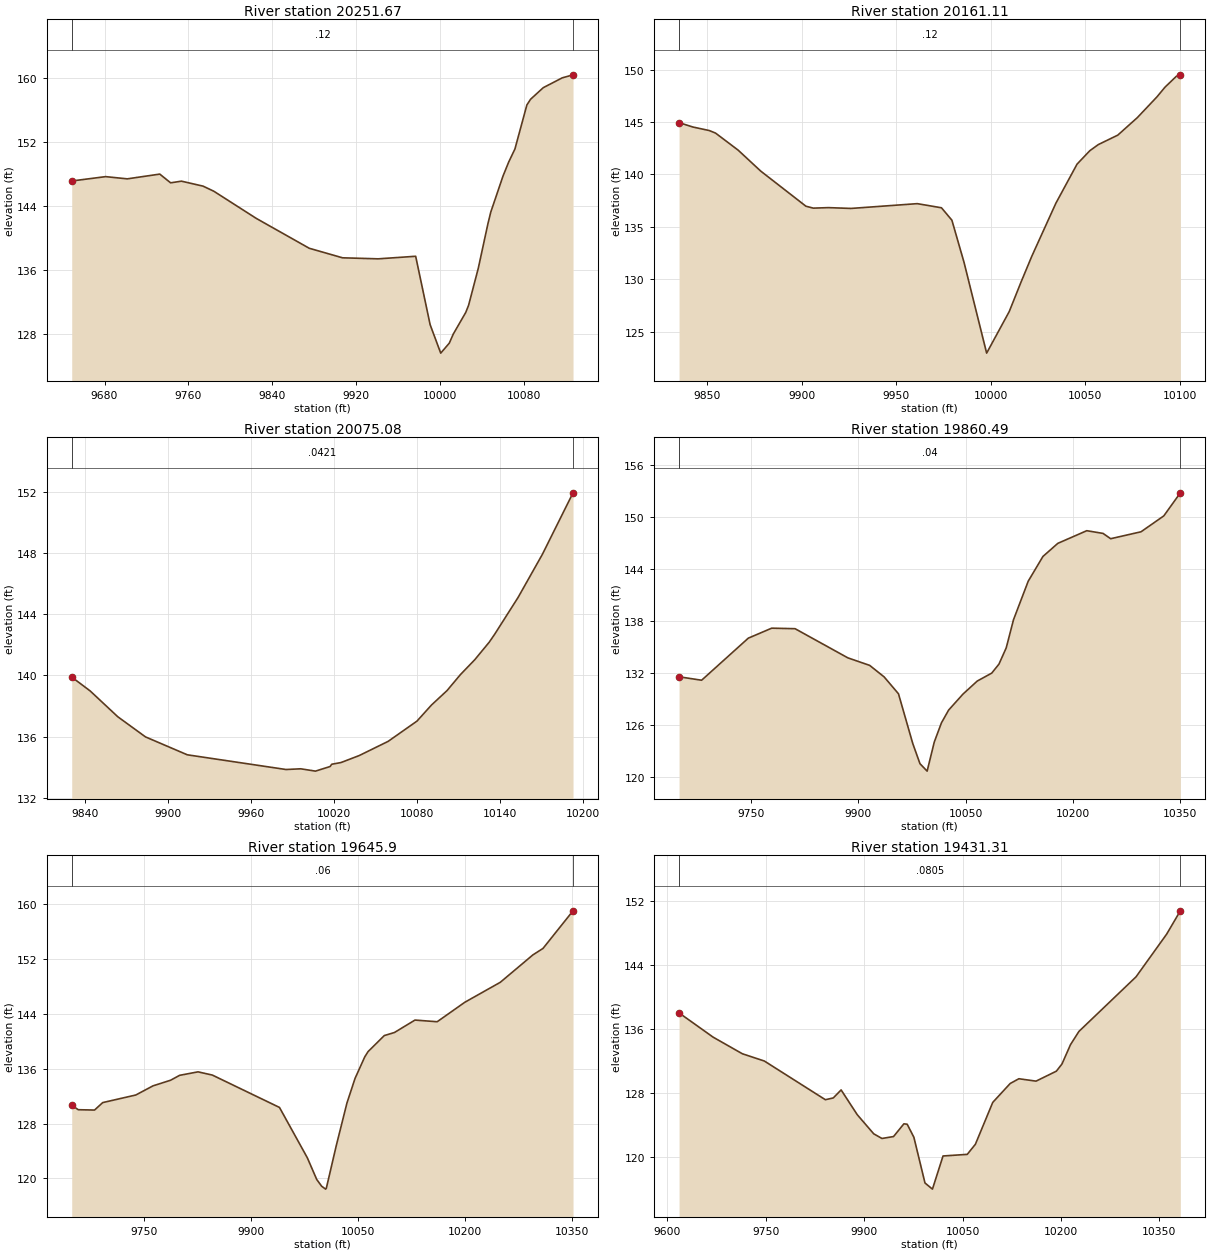
Type RM Length L Ch R = 1 ,20251.67,90.566900,90.566900,90.566900
XS GIS Cut Line= 6
442776.291525251734910.942176524442620.956719503734948.767587383
442550.876659102734947.008131878442504.405829588734927.956761303
442401.031751249734860.929496812442335.638027184734827.160522632
#Sta/Elev= 30
9648.762147.13339681.054147.67929701.693147.40119732.652147.99739742.972146.9027
9753.291147.11119773.887146.48849784.102145.85249824.681142.4356 9875.03138.6981
9906.763137.4997 9940.74137.37059976.464137.69269990.241129.112210000.33125.5458
10008.52126.799710012.25127.925610024.17130.648910026.89131.550810036.09 136.174
10045.26141.746210048.01143.232510059.62147.731210065.09149.511610071.02 151.143
10082.42156.669910085.92157.380910098.03158.835910116.04160.064910126.38160.4473
#Mann= 3 , 0 , 0
9648.762    0.12       09648.762    0.12       010126.38    0.12       0
#XS Ineff= 2 , 0
       09925.393                       0
Bank Sta=9648.762,10126.38
Exp/Cntr=0.3,0.1

Type RM Length L Ch R = 1 ,20161.11,86.031300,86.031300,86.031300
XS GIS Cut Line= 3
442631.152898669734903.723320678442449.337355852734785.211974978
442402.963351011734796.989500001
#Sta/Elev= 28
9835.285144.9387 9842.63144.5206 9851.26144.18589854.567143.94329866.504 142.318
 9878.44140.31949902.314 136.9729906.199136.78799914.251136.83529926.188 136.759
9961.138137.21519973.935 136.8229979.451135.63599985.871131.61259997.808122.9623
10009.75126.928510016.08129.777810021.68132.203910034.39137.254510045.56140.9777
10052.31142.261110056.79142.844310067.11143.749310077.42145.415810087.74147.3849
10092.08148.326810098.06149.360110100.16149.4989
#Mann= 3 , 0 , 0
9835.285    0.12       09835.285    0.12       010100.16    0.12       0
#XS Ineff= 2 , 0
       09933.605                       0
Bank Sta=9835.285,10100.16
Exp/Cntr=0.3,0.1

Type RM Length L Ch R = 1 ,20075.08,214.587000,214.587000,214.587000
XS GIS Cut Line= 6
442718.275971234734767.922794163442657.234871179734771.698532328
442580.461528778734761.629897237 442527.60119462734742.751206502
442382.235275805734786.801484913442366.503033578734789.318643674
#Sta/Elev= 23
9830.502139.88279843.803138.98079863.841137.29039883.879135.97539914.085134.8073
9985.508133.84639996.127133.892710006.75 133.74110017.36 134.04210018.53134.1897
10025.22134.301210038.39134.756510059.29 135.68210080.18137.006810090.63138.0532
10101.94 139.00210111.53140.036510121.98141.016710132.43142.160610136.42142.6856
10153.33145.0873 10170.9147.902310193.05151.9178
#Mann= 3 , 0 , 0
9830.502  0.0421       09830.502  0.0421       010193.05  0.0421       0
#XS Ineff= 2 , 0
       09951.401                       0
Bank Sta=9830.502,10193.05
Exp/Cntr=0.3,0.1

Type RM Length L Ch R = 1 ,19860.49,214.587000,214.587000,214.587000
XS GIS Cut Line= 6
442923.958321195 734647.00232072442718.455860619734563.923340592
442657.645046566734552.705216951442476.234807301734542.568525955
442390.511471272734519.936704677442253.226529968734471.658535193
#Sta/Elev= 30
9650.064131.56569681.552131.16699746.795136.01679779.416137.16469812.037137.1049
9885.651133.74889916.226132.8771 9936.39131.55089956.416129.60739976.427123.8618
9986.427121.55369996.428120.695710006.43124.056210016.43126.261610026.43127.7266
10046.43129.5665 10066.5 131.07810086.61131.986610096.73 133.02610106.86134.8993
   10117138.131910137.54142.573310158.08145.423410178.89146.936810219.31148.3934
10242.07148.080610252.67147.470510295.07 148.26910326.88150.101610349.96152.7571
#Mann= 3 , 0 , 0
9650.064    0.04       09650.064    0.04       010349.96    0.04       0
#XS Ineff= 2 , 0
       0                               0
Bank Sta=9650.064,10349.96
Exp/Cntr=0.3,0.1

Type RM Length L Ch R = 1 , 19645.9,214.587000,214.587000,214.587000
XS GIS Cut Line= 6
442942.913839746734605.034340118442804.620109971734516.564663951
442753.129608694734468.350494077442585.859470695734282.382394846
 442503.16923379734216.146814759442409.356193355734155.031710031
#Sta/Elev= 30
9648.354130.71339657.429130.03599680.364129.98579691.831131.0745 9738.27132.1828
9762.389133.51719787.101 134.3389799.719 135.0529825.567 135.5619845.633135.0904
9939.846130.36729978.912 123.023 9992.13119.8515    9999118.874810004.56118.4488
10005.57118.577310019.55124.808810034.53131.025610045.88134.610810059.54137.7545
10064.08138.507410086.88140.8527 10101.2141.305310129.95143.1153 10161.1142.8723
10199.86 145.71310249.62148.624710295.46 152.63110309.56153.568310351.69159.0557
#Mann= 3 , 0 , 0
9648.354    0.06       09648.354    0.06       010351.69    0.06       0
#XS Ineff= 2 , 0
       0                               0
Bank Sta=9648.354,10351.69
Exp/Cntr=0.3,0.1

Type RM Length L Ch R = 1 ,19431.31,214.587100,214.587100,214.587100
XS GIS Cut Line= 6
443192.662790861734508.721582801443063.917633949734447.773159631
442965.333403647734386.383175481442905.480294977734340.790646879
442692.880285957 734161.54346243442569.407115403734073.098211644
#Sta/Elev= 30
9617.874138.01279669.854134.98789714.351132.92139747.959132.01299840.956127.1934
9852.956127.41269864.957128.41249889.547125.32679914.689122.94099927.259122.3631
9944.851122.60149960.638124.18849965.667124.14039975.905122.50699992.819116.8143
10004.19116.050610020.31120.181310057.24120.382710069.65121.641610096.11126.8571
10122.68129.212510135.97129.806910162.09129.508310193.07130.747910201.69 131.651
10214.58134.043410227.48 135.70210314.55142.507310361.19147.820510382.12150.7331
#Mann= 3 , 0 , 0
9617.874  0.0805       09617.874  0.0805       010382.12  0.0805       0
#XS Ineff= 2 , 0
       09975.323                       0
Bank Sta=9617.874,10382.12
Exp/Cntr=0.3,0.1

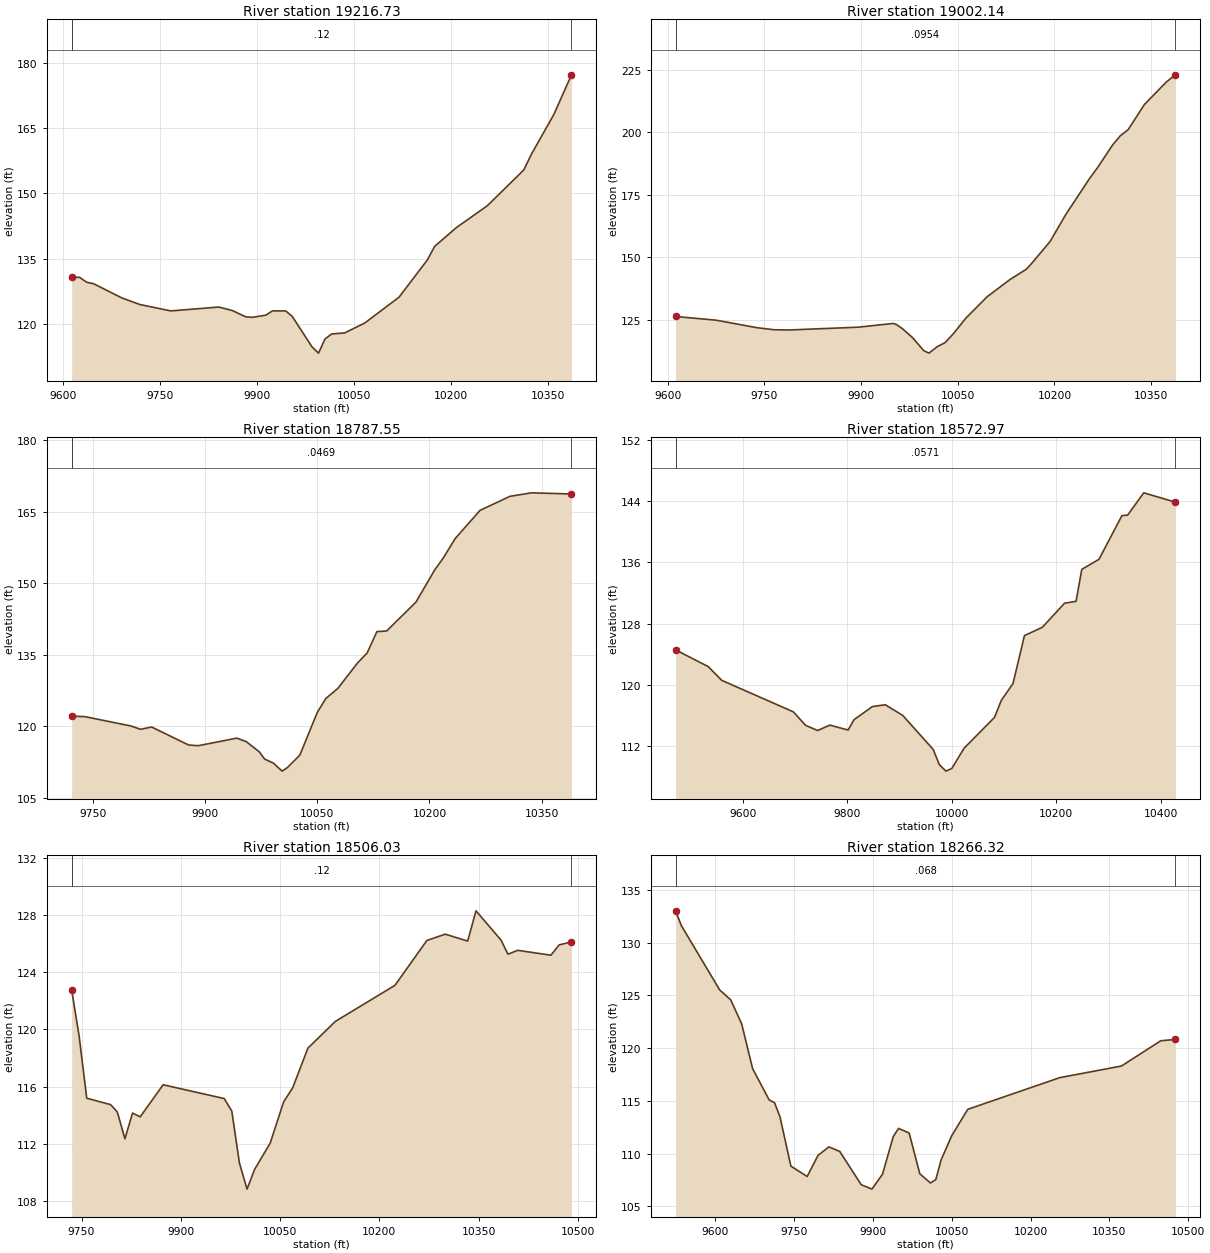
Type RM Length L Ch R = 1 ,19216.73,214.587000,214.587000,214.587000
XS GIS Cut Line= 6
443276.250076169734226.018256668443048.015521772734136.463637844
442873.037428885734101.466149898442802.268234677734079.734856471
442705.231193083734033.664203596442561.623912039 733948.84995125
#Sta/Elev= 30
9613.853130.68789626.067130.68819636.923129.5585 9647.78129.21139691.207125.9597
9719.207124.43179766.944122.96449841.283123.85149862.269 123.0399882.905121.6024
9893.224121.4847 9913.86121.98399924.179122.96929944.714122.95399954.829121.6699
9985.172114.71929995.287113.2593 10005.4116.524310015.54117.657710035.81117.9048
10066.83120.186410119.78126.128110163.45134.672710174.69137.785610208.39142.1171
10256.06147.124710312.54155.367510324.15158.946710358.99168.120810386.14177.2214
#Mann= 3 , 0 , 0
9613.853    0.12       09613.853    0.12       010386.14    0.12       0
#XS Ineff= 2 , 0
       09929.779                       0
Bank Sta=9613.853,10386.14
Exp/Cntr=0.3,0.1

Type RM Length L Ch R = 1 ,19002.14,214.587000,214.587000,214.587000
XS GIS Cut Line= 6
443309.645286813734114.879276684443167.511832329734038.457023368
443073.619300584733981.847550793443019.093569467733943.640852823
442825.132731141733796.954294516442663.613324591733688.629946602
#Sta/Elev= 30
 9612.37126.34999675.464 124.8579738.813121.85439765.244121.04959788.356120.9547
9895.317122.06239949.963123.56329955.101123.1092 9964.26121.46289980.205117.8128
9997.352112.665910005.35 111.69510017.98114.237510030.62115.937310043.26119.4725
10062.81125.748410095.52134.217710131.34141.180510156.13145.198310162.63146.9487
10193.32156.357610217.66 167.15410254.17181.416210266.78185.840710290.45195.0181
 10302.4198.666610314.34201.031810339.44211.086710374.06220.236710387.66222.9832
#Mann= 3 , 0 , 0
 9612.37  0.0954       0 9612.37  0.0954       010387.66  0.0954       0
#XS Ineff= 2 , 0
       0                               0
Bank Sta=9612.37,10387.66
Exp/Cntr=0.3,0.1

Type RM Length L Ch R = 1 ,18787.55,214.587000,214.587000,214.587000
XS GIS Cut Line= 6
443349.282999101733928.606681949443262.145298435733864.196501671
443169.138215536733787.982969877443086.059292205733732.343423834
442938.267128107733610.437123977442816.952431059733525.083237451
#Sta/Elev= 30
9721.338122.11499738.792122.01779800.814120.04719813.465119.35329828.415119.8312
 9877.75116.06799890.679115.91939942.393117.50539955.045116.76479972.416114.6217
9979.503113.1169 9991.22112.272510002.92110.587810010.12111.354510026.59113.9396
10050.03122.924710061.46125.8221 10077.5 127.939 10103.6133.226310116.64135.3579
10129.69139.834310142.74139.967610181.88146.002110207.47152.876610218.23155.1933
10234.29159.3082 10267.7165.253610307.71168.191210336.39168.926610389.99168.6839
#Mann= 3 , 0 , 0
9721.338  0.0469       09721.338  0.0469       010389.99  0.0469       0
#XS Ineff= 2 , 0
       09934.986                       0
Bank Sta=9721.338,10389.99
Exp/Cntr=0.3,0.1

Type RM Length L Ch R = 1 ,18572.97,66.931700,66.931700,66.931700
XS GIS Cut Line= 4
443738.717657447733890.135259107443314.709052026733637.955250144
 443200.77676037733565.255597353442901.698711753733430.026767462
#Sta/Elev= 30
 9471.26124.5425 9533.76122.35439559.557120.5589 9696.65116.4349 9719.92114.6731
 9743.19 113.991 9766.46 114.7019801.365114.0536    9813115.42179847.905117.1243
9872.561117.3633 9906.08115.96549964.255 111.5169976.111  109.529988.678108.6752
9999.836109.017410023.56111.683910081.63115.705710094.73117.942510117.06120.1356
10139.01126.420310173.18127.501110215.83130.657910237.78 130.90710248.76 135.088
10281.68136.403710325.58142.124710336.55142.189910367.36145.105410427.97143.8834
#Mann= 3 , 0 , 0
 9471.26  0.0571       0 9471.26  0.0571       010427.97  0.0571       0
#XS Ineff= 2 , 0
       0  9974.5        10018.82       0
Bank Sta=9471.26,10427.97
Exp/Cntr=0.3,0.1

Type RM Length L Ch R = 1 ,18506.03,239.712900,239.712900,239.712900
XS GIS Cut Line= 5
443544.743774265733694.378861234443352.686482608733583.701777905
443217.052802026733506.661847383443061.887871534733402.495180681
442910.322643101733286.830011636
#Sta/Elev= 30
9735.098122.76729746.344119.55059757.886115.18599793.938 114.7349804.052114.2254
9815.594 112.3469827.135114.14589838.677113.88039873.302 116.1259965.603115.1602
9977.104114.27989988.604110.6491 10000.1108.820610011.61110.209210035.12112.0418
10055.37 114.92510069.11115.917310092.11118.691610133.67120.562910223.62123.0848
 10271.8126.222410299.64126.666110333.46126.180510346.04128.298910383.78126.2559
10394.41125.263310408.94125.533910459.25125.194510471.83125.917510490.29126.1187
#Mann= 3 , 0 , 0
9735.098    0.12       09735.098    0.12       010490.29    0.12       0
#XS Ineff= 2 , 0
       09970.673        10018.71       0
Bank Sta=9735.098,10490.29
Exp/Cntr=0.3,0.1

Type RM Length L Ch R = 1 ,18266.32,239.712900,239.712900,239.712900
XS GIS Cut Line= 6
443825.311218458733445.073192373443530.013153987733360.110723845
443259.716736002733312.180923925443180.705164646733293.967857482
443072.487728922733259.829717073442909.070522783 733197.06438839
#Sta/Elev= 30
9524.242133.01969535.017 131.629 9608.16125.51979629.058124.58529649.956122.3116
9670.854118.05849702.201115.10569712.605 114.8269722.951113.49019743.642108.8236
9774.679107.8373 9795.37109.83939816.061110.64429836.683110.21549877.518107.0624
9897.908  106.649918.178108.05359938.447111.60839948.582112.39899968.852 111.959
9989.122108.094410009.41107.223310019.56107.543710029.71109.418210050.01111.7132
10080.45114.206210255.82117.209510372.98118.308910447.97120.705610475.74120.8255
#Mann= 3 , 0 , 0
9524.242   0.068       09524.242   0.068       010475.74   0.068       0
#XS Ineff= 2 , 0
       09882.443                       0
Bank Sta=9524.242,10475.74
Exp/Cntr=0.3,0.1

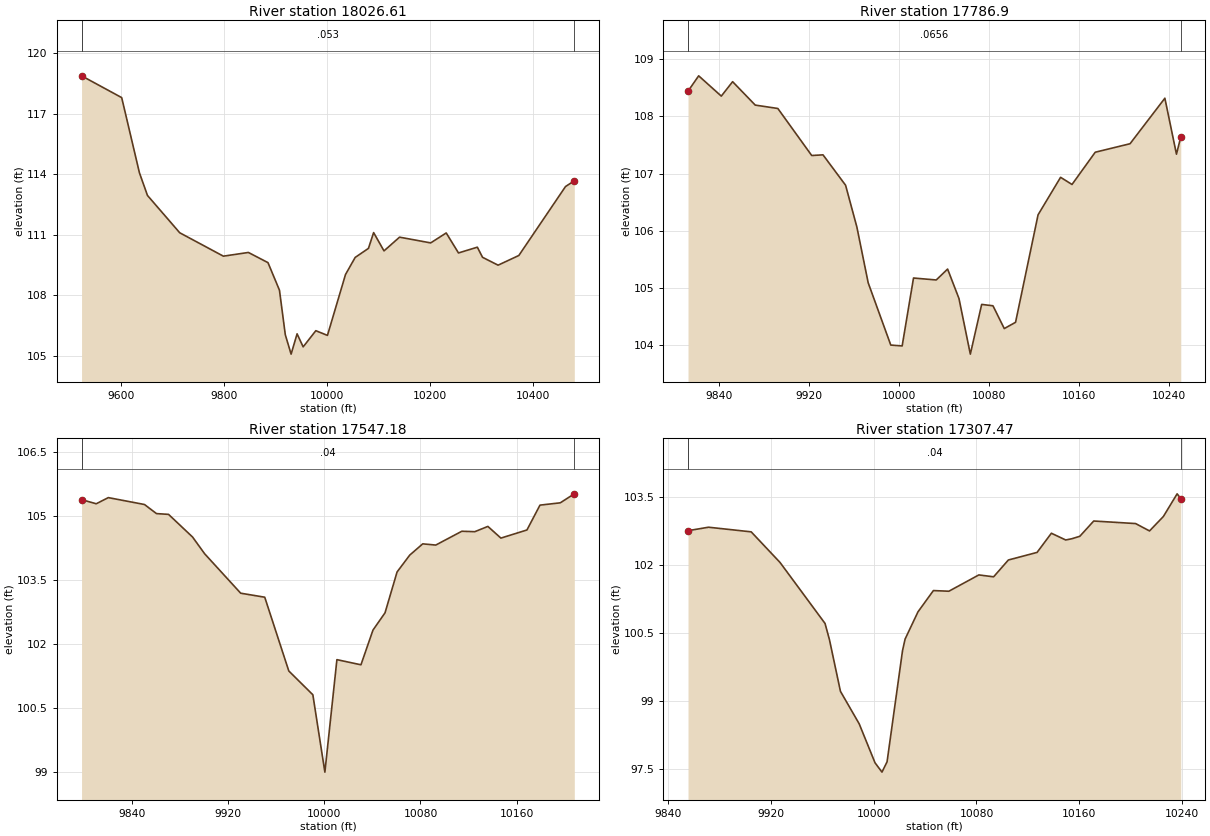
Type RM Length L Ch R = 1 ,18026.61,239.712900,239.712900,239.712900
XS GIS Cut Line= 6
 443867.64945969  733277.6029495443684.341407806733222.123554319
 443559.68091175733176.469910234443481.499986231733138.394918099
443368.751049489733068.790327147442958.012555093733016.643706784
#Sta/Elev= 30
 9522.44118.87219600.467117.79359634.988114.06639650.584112.94859713.271111.1005
9798.116109.94189846.743110.12519884.817109.62189907.162108.25589918.473106.0538
9929.784105.09079941.411106.0951 9953.21105.45019977.828106.251110000.42106.0185
10035.53109.033210054.29109.878810080.11110.327110090.19111.108510110.35110.2032
10140.59110.882610201.07110.598610231.31111.090710255.14 110.101 10291.8110.3863
10301.88109.885510332.12109.495510372.44109.974710463.16113.388610480.28113.6728
#Mann= 3 , 0 , 0
 9522.44   0.053       0 9522.44   0.053       010480.28   0.053       0
#XS Ineff= 2 , 0
       0                               0
Bank Sta=9522.44,10480.28
Exp/Cntr=0.3,0.1

Type RM Length L Ch R = 1 , 17786.9,239.712900,239.712900,239.712900
XS GIS Cut Line= 6
443694.415800691732904.485369906443518.426751912732889.159188583
 443437.24162972732900.117124766443404.845907599732902.818812236
443359.833075851 732902.77437444443261.287101895732927.461648002
#Sta/Elev= 30
 9812.65108.43889822.114108.70779842.218108.3532 9852.27108.60539872.369108.1959
9892.433 108.1379922.528107.3149 9932.56107.32649952.624106.79519962.656106.0641
9972.688105.09049992.755104.001510002.87 103.98610012.96105.173510033.15105.1392
10043.24  105.3310053.34104.815610063.43103.843110073.51104.712110083.54104.6881
10093.58104.289810103.61104.399410123.61106.278710143.61106.933710153.76106.8087
10174.38107.372210205.31107.520810236.24108.316410246.54107.338210250.37107.6389
#Mann= 3 , 0 , 0
 9812.65  0.0656       0 9812.65  0.0656       010250.37  0.0656       0
#XS Ineff= 2 , 0
       0                               0
Bank Sta=9812.65,10250.37
Exp/Cntr=0.3,0.1

Type RM Length L Ch R = 1 ,17547.18,239.712800,239.712800,239.712800
XS GIS Cut Line= 6
443677.122445554732699.270888925443603.516177893732693.223700881
443555.321965277732691.923282146443441.066456914732696.182834461
443410.933406144732694.154994309443278.648212999732749.510259107
#Sta/Elev= 29
9797.973105.37889810.193105.28239820.242105.42659850.314105.26519860.337105.0517
9870.361105.03359890.372104.50179900.375104.11069930.391103.18529950.407103.0912
9970.424101.3616 9990.44 100.80410000.4598.9898910010.46101.627110030.46101.5065
10040.48102.3207 10050.5102.725310060.52103.683110071.03104.077410081.87104.3423
10092.71104.313810114.39104.637510125.23104.627910136.07104.751410146.91104.4771
10168.59104.667610179.43  105.2510196.32105.3044   10208105.5153
#Mann= 3 , 0 , 0
9797.973    0.04       09797.973    0.04       0   10208    0.04       0
#XS Ineff= 2 , 0
       0                               0
Bank Sta=9797.973,10208
Exp/Cntr=0.3,0.1

Type RM Length L Ch R = 1 ,17307.47,234.212400,234.212400,234.212400
XS GIS Cut Line= 6
443689.729938808732548.583006241443624.799167603732517.965376705
443508.546614826732441.755432278  443473.9094612732422.067742497
443430.826504827732400.865840212443352.352616906732368.327610552
#Sta/Elev= 30
9855.383102.74989871.354102.82629904.573102.72429926.989102.05179962.076100.7067
9965.509100.34979974.073  99.2129988.67698.49593   1000197.6376110006.4297.43209
10010.3897.6601510022.41100.107210024.42100.362910034.44100.961910046.46101.4308
10058.49101.416210081.84101.775610093.34101.733910104.84102.104210127.17102.2713
10138.32102.693610149.46102.545410154.11102.571210160.44 102.626 10171.3102.9629
10203.89102.906710214.75102.744510225.55103.062910236.24103.561710239.08103.4572
#Mann= 3 , 0 , 0
9855.383    0.04       09855.383    0.04       010239.08    0.04       0
#XS Ineff= 2 , 0
       0                               0
Bank Sta=9855.383,10239.08
Exp/Cntr=0.3,0.1