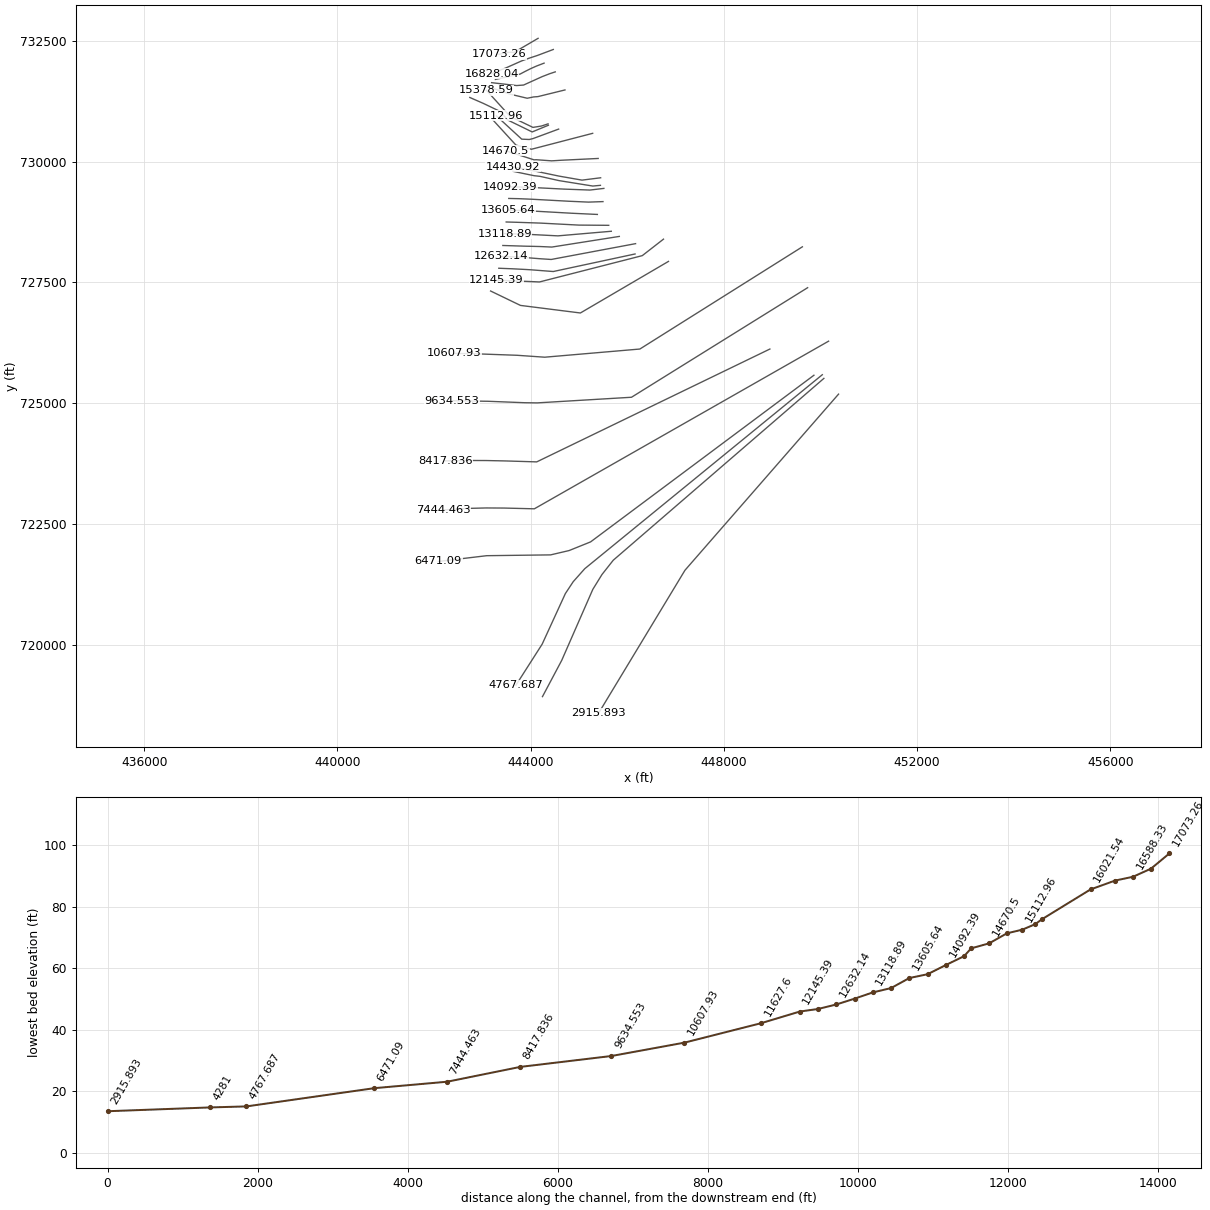
HEC-RAS study 708_ras.prj: 708

--- 708_ras.g01 (geometry) --- (continued)

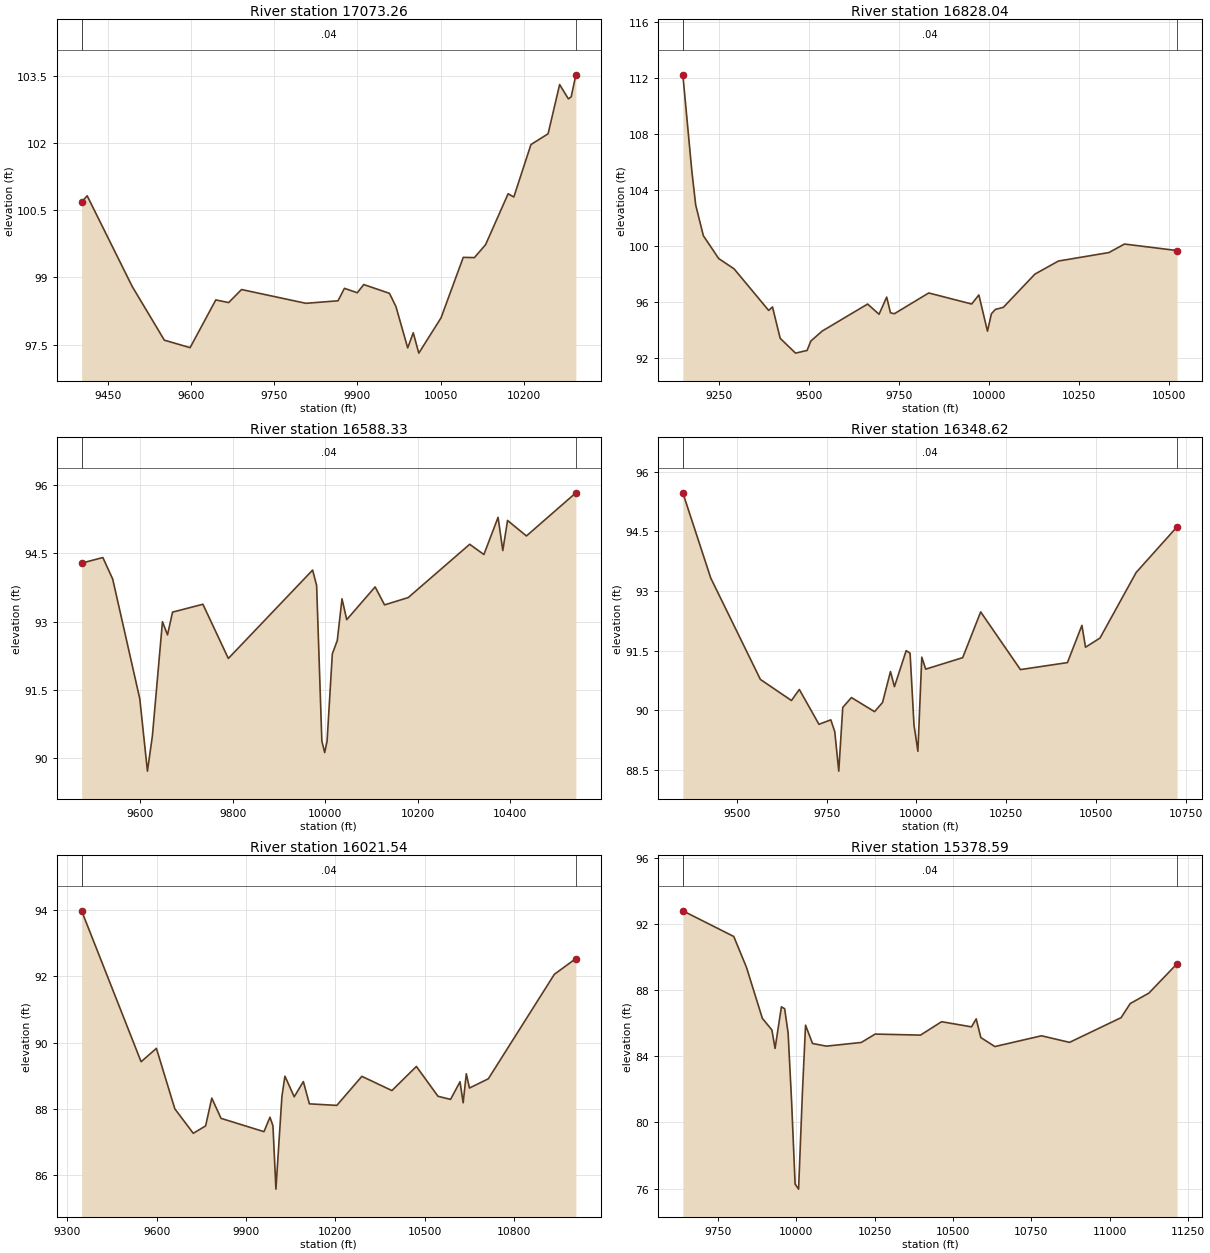
Type RM Length L Ch R = 1 ,17073.26,245.213400,245.213400,245.213400
XS GIS Cut Line= 6
444153.609923303732552.776098296443656.994612396732262.320550814
443582.868726552732264.137079164443508.428005934732259.295492396
443460.739120752732250.974710882443346.897803247732221.263023973
#Sta/Elev= 30
9403.136100.68559413.111100.82429494.20498.799689552.12897.599779598.46797.43216
9644.80698.497899667.97698.439089691.14698.730399806.99498.422679864.91798.47857
9876.50298.757299899.67298.658519911.25798.841619957.59698.645349969.18198.35331
9990.45197.4275510000.4597.7642810010.4597.3101210050.4798.09734 10090.599.44834
 10110.699.4432210130.7499.7326710171.34100.869210181.57100.796710212.43101.9678
 10243.3102.2084 10264.1103.308310279.86102.988910284.92103.033510293.35103.5252
#Mann= 3 , 0 , 0
9403.136    0.04       09403.136    0.04       010293.35    0.04       0
#XS Ineff= 2 , 0
       09827.126                       0
Bank Sta=9403.136,10293.35
Exp/Cntr=0.3,0.1

Type RM Length L Ch R = 1 ,16828.04,239.712900,239.712900,239.712900
XS GIS Cut Line= 6
 444468.42922172732322.199262351444140.425728917732198.565962687
443974.972439647732144.144788146443813.194071025732085.533578619
443487.137116581731940.433357358443188.415166974731821.132470727
#Sta/Elev= 30
9148.337112.23379173.375105.34379184.062102.93469205.436100.73599248.18399.10282
 9290.9398.369979387.11195.398699397.79895.647269419.171 93.40729461.91892.34748
9493.97992.538189504.57993.21393 9536.16  93.9259662.48595.854749694.28495.12465
9715.55696.351199726.192 95.22779736.82895.161399832.55296.645879951.95295.85719
9972.08896.503569996.02693.9159110007.0395.1630710018.0695.4711710040.1195.61713
10127.9997.9923210193.4698.9280910334.0799.5340410377.16 100.14210523.72 99.6773
#Mann= 3 , 0 , 0
9148.337    0.04       09148.337    0.04       010523.72    0.04       0
#XS Ineff= 2 , 0
       09635.474        10152.39       0
Bank Sta=9148.337,10523.72
Exp/Cntr=0.3,0.1

Type RM Length L Ch R = 1 ,16588.33,239.712900,239.712900,239.712900
XS GIS Cut Line= 6
444278.072025985732039.461246386444125.870208323731981.264160454
444000.101824284731925.571720526 443884.15634653731867.319225743
443781.093757451731812.875342712443270.512555033731702.407595694
#Sta/Elev= 30
9473.17594.286389519.08394.40924  9540.493.935529598.98891.304879615.54889.71398
9626.31190.492359648.02592.999249658.96292.709729669.89893.209299735.51893.38225
9790.58592.190849972.89594.133889981.57293.794119992.86990.37655    999990.12243
10004.1990.3732810015.5392.2914210026.2492.5850310036.4793.50233 10046.793.04375
10108.0993.7637210128.5593.3684110179.7193.5292510312.7194.7007210343.4194.47581
 10374.195.2930410384.3394.5629910394.5795.2245110435.4994.88398 10542.495.83178
#Mann= 3 , 0 , 0
9473.175    0.04       09473.175    0.04       0 10542.4    0.04       0
#XS Ineff= 2 , 0
       09568.659        10142.22       0
Bank Sta=9473.175,10542.4
Exp/Cntr=0.3,0.1

Type RM Length L Ch R = 1 ,16348.62,327.073900,327.073900,327.073900
XS GIS Cut Line= 6
444508.626209289731858.612157837 444388.40746358 731818.48696278
444236.648983151731759.527755037443853.248815835731585.932506636
443709.192262501 731575.37014465443191.805885315731635.411850855
#Sta/Elev= 30
9349.82795.469269427.446  93.326 9565.6190.774129652.13890.242439674.02390.52083
9728.735 89.64399761.67889.756389772.75189.458549783.82488.465849794.89690.06781
9819.08290.317059883.477 89.96269905.62290.192419927.76890.97082 9938.8490.59129
9971.48691.498019982.36491.434259993.24189.6277910004.0888.9654410014.9591.33396
10025.8291.0322110128.7691.3213210178.8992.4724810289.5391.02071 10420.491.19717
10460.6792.1337210470.7491.58417   1051191.8147510611.6893.4650910725.6394.61487
#Mann= 3 , 0 , 0
9349.827    0.04       09349.827    0.04       010725.63    0.04       0
#XS Ineff= 2 , 0
       0                10204.77       0
Bank Sta=9349.827,10725.63
Exp/Cntr=0.3,0.1

Type RM Length L Ch R = 1 ,16021.54,642.953900,642.953900,642.953900
XS GIS Cut Line= 6
444710.121063143 731484.51941891444150.234687984731346.680518717
444060.180816203731339.798304528 443928.34635359 731312.73328191
443566.288327068 731399.11175549443106.630762935 731555.65389961
#Sta/Elev= 30
9347.75293.964249547.54289.422459598.90589.825879660.79288.005919722.80487.26908
9764.22487.492259784.93588.32788    981687.719099960.22987.318229980.35887.75344
9990.358 87.495810000.3685.5890110020.4488.3728710030.56 88.988610061.8388.36753
10092.4588.8258310112.7788.1555710204.8588.1087510289.0588.98324 10389.988.55564
10472.1589.2808810544.7288.3831710586.9788.2895610618.6688.8197510629.2388.18723
10639.7989.0613310650.3688.6310510713.74 88.908910935.5892.0538211007.8192.52783
#Mann= 3 , 0 , 0
9347.752    0.04       09347.752    0.04       011007.81    0.04       0
#XS Ineff= 2 , 0
       0                10321.87       0
Bank Sta=9347.752,11007.81
Exp/Cntr=0.3,0.1

Type RM Length L Ch R = 1 ,15378.59,94.523100,94.523100,94.523100
XS GIS Cut Line= 6
444359.856319897730782.742912338444222.538327038730737.653422147
444046.910376012730709.421425432443634.142131925730908.472101569
443570.614203364730941.695187882443084.517493755 731477.23675549
#Sta/Elev= 30
9638.82292.781069801.11791.23147 9841.6389.367329892.272 86.28359922.65785.58241
9932.78684.467759953.04286.981449963.35786.861219974.45985.382529985.56181.23467
9996.66376.2694310007.7675.9638110020.1281.8675210029.9785.8719210052.17 84.7647
10096.5884.60431 10207.6  84.82710252.0185.3337110396.34 85.270610463.6686.08113
10559.0585.7697710573.9386.2499210588.8185.1228110633.4584.5798710782.23 85.2299
10871.5184.8326211035.8586.3243111064.9387.1768911124.4587.8071711214.4489.58664
#Mann= 3 , 0 , 0
9638.822    0.04       09638.822    0.04       011214.44    0.04       0
#XS Ineff= 2 , 0
       0                10302.03       0
Bank Sta=9638.822,11214.44
Exp/Cntr=0.3,0.1

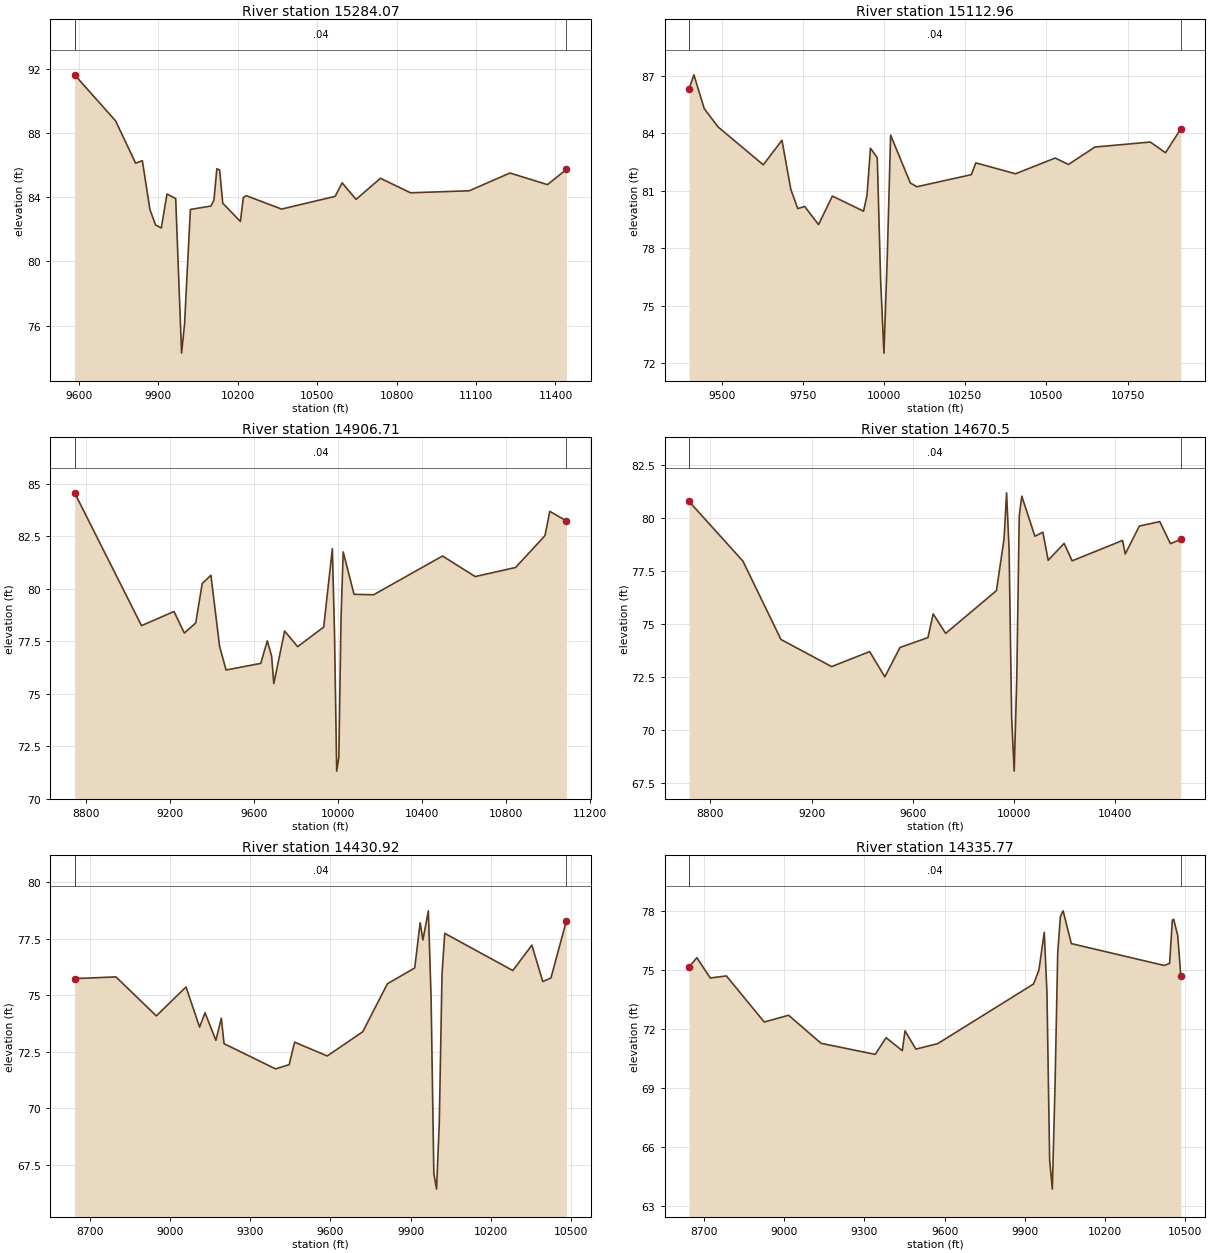
Type RM Length L Ch R = 1 ,15284.07,171.108100,171.108100,171.108100
XS GIS Cut Line= 6
444367.069577128730754.146477699444031.139862388730615.177790165
443523.922062933730862.937417299443376.180701613731035.882072255
443017.677215964731207.271477684442739.899438143 731328.79925549
#Sta/Elev= 30
9584.94891.627029739.49688.759189815.24586.121189840.64886.278619869.04683.24305
9890.56682.272099912.08682.087229933.60684.201589966.43883.920559988.64274.28947
9999.74476.0735410021.9583.2397410099.6683.4541910110.7683.8292810121.8785.77607
10132.2985.7032110144.0783.6299310210.6882.4907910221.7883.9804610232.8984.09815
10366.1183.2631510568.3784.0555110594.6884.8967710647.2983.8679310739.3585.18093
10852.6684.2782411074.3484.4021111228.12 85.509311370.0284.7868111441.0885.73163
#Mann= 3 , 0 , 0
9584.948    0.04       09584.948    0.04       011441.08    0.04       0
#XS Ineff= 2 , 0
       0 9804.55        10276.56       0
Bank Sta=9584.948,11441.08
Exp/Cntr=0.3,0.1

Type RM Length L Ch R = 1 ,15112.96,206.250300,206.250300,206.250300
XS GIS Cut Line= 5
444578.875132591 730674.28536658444044.152910382730476.368699908
443971.236243725730459.007588819443814.986243725730465.952033252
443290.246660441730948.590922147
#Sta/Elev= 30
9399.44186.311629414.23687.051729446.22585.281959488.877 84.32719627.853 82.3512
9685.47183.632449712.80181.064799734.12780.065749755.45380.174029798.10579.22841
9840.75780.718179936.72479.929479947.38780.75627 9958.0583.215839979.02582.71833
9989.30476.342589999.58472.5138710009.86 77.573210020.1483.9027110080.8481.40214
10100.8681.2050610268.8981.8372410282.4882.4526410404.7681.8825410527.0482.70553
 10567.882.3703510649.3283.2787910819.99 83.5402 10866.782.9826210913.9284.22817
#Mann= 3 , 0 , 0
9399.441    0.04       09399.441    0.04       010913.92    0.04       0
#XS Ineff= 2 , 0
       09769.338                       0
Bank Sta=9399.441,10913.92
Exp/Cntr=0.3,0.1

Type RM Length L Ch R = 1 ,14906.71,236.210700,236.210700,236.210700
XS GIS Cut Line= 4
445283.302215964 730586.61175549444015.941104829730256.750644371
443694.760549307730343.556199923443221.670271486730860.049255475
#Sta/Elev= 30
8745.536 84.5654 9064.1178.240939219.10778.913899268.04977.886599322.43978.36702
9353.43880.247099394.771 80.63889436.10477.260499467.103 76.12759632.43476.44384
9663.43377.51685  9684.176.786639694.43375.478869746.09877.983619808.09777.23955
9932.09578.171649973.42881.906639983.76177.826729994.09471.3121710004.4371.98515
10014.76 78.595910025.0981.7502110076.81 79.731910170.0479.7116410498.2781.55626
10653.9680.5770410846.4381.0111810986.4782.5295211009.2883.6828311088.2483.23127
#Mann= 3 , 0 , 0
8745.536    0.04       08745.536    0.04       011088.24    0.04       0
#XS Ineff= 2 , 0
       0 9716.55                       0
Bank Sta=8745.536,11088.24
Exp/Cntr=0.3,0.1

Type RM Length L Ch R = 1 , 14670.5,239.583100,239.583100,239.583100
XS GIS Cut Line= 6
445397.555473506730066.411272556444648.548760265730029.933672875
444434.275780529730017.099324733444114.671554178730040.187792152
444070.152117252 730037.88344422443485.790332824730224.977040127
#Sta/Elev= 30
 8716.0280.796188928.82777.977249079.00574.276939279.24272.99571 9429.4273.70481
9489.50572.512699549.613 73.9007 9659.8174.365779680.57175.485199729.97574.56546
9930.49776.583599960.57579.019179970.60181.204229980.62778.492939990.65370.58037
10000.6868.0586710010.6972.3079310020.7180.1075510030.7281.04588 10082.5 79.1521
   1011479.34615   1013578.01759   1019878.81732 10229.577.99169   1042978.95528
 10439.578.3164810495.2779.63495   1057679.84543   1061878.8048710659.1779.00238
#Mann= 3 , 0 , 0
 8716.02    0.04       0 8716.02    0.04       010659.17    0.04       0
#XS Ineff= 2 , 0
       09657.216                       0
Bank Sta=8716.02,10659.17
Exp/Cntr=0.3,0.1

Type RM Length L Ch R = 1 ,14430.92,95.148200,95.148200,95.148200
XS GIS Cut Line= 5
445448.232771486729666.472866595445062.583750725729618.030368894
 444585.54238537729701.323305696444047.347940922729814.170527905
443638.306533903729892.007533506
#Sta/Elev= 30
8643.15575.732978797.59275.808128948.771 74.08589059.83575.362979110.59273.58991
9130.89474.22384  9171.573.006099191.802 73.98549201.95472.857689394.828 71.7423
9445.58471.931689465.88772.923419588.16972.314869720.99673.386679812.95375.50353
9915.12876.201289935.56378.20219 9945.7877.440939966.21578.727079976.433  74.887
 9986.6567.121169996.86866.4311910007.0969.36501 10017.375.9265210027.5277.73195
10282.1576.0880310353.41 77.211110394.1275.6016710424.6675.7604910482.3778.28214
#Mann= 3 , 0 , 0
8643.155    0.04       08643.155    0.04       010482.37    0.04       0
#XS Ineff= 2 , 0
       09618.193                       0
Bank Sta=8643.155,10482.37
Exp/Cntr=0.3,0.1

Type RM Length L Ch R = 1 ,14335.77,243.374800,243.374800,243.374800
XS GIS Cut Line= 6
445443.892493725 729510.22286658445286.648092598729495.360368043
 444585.64271009729608.121119916444193.181274265729696.114972368
444070.931128561 729709.65987654443633.826282978729800.151633486
#Sta/Elev= 30
8643.99875.148968673.01975.629798723.24274.59668 8783.51 74.70358925.15572.36295
9016.31272.705719137.85571.280459340.42670.71931 9380.94  71.5679441.71170.90642
 9451.8471.914999492.35470.986459574.10871.264889932.45874.29101 9952.5874.98612
9972.70276.916089982.76373.860519992.82565.3593710002.8963.8778510012.9569.11415
10023.0175.8521210033.0777.7156910043.2478.00778   1007476.3442110421.2475.23388
10441.6275.3372710451.8177.5395410456.7877.5771110472.1976.7389710483.5874.69322
#Mann= 3 , 0 , 0
8643.998    0.04       08643.998    0.04       010483.58    0.04       0
#XS Ineff= 2 , 0
       09605.384                       0
Bank Sta=8643.998,10483.58
Exp/Cntr=0.3,0.1

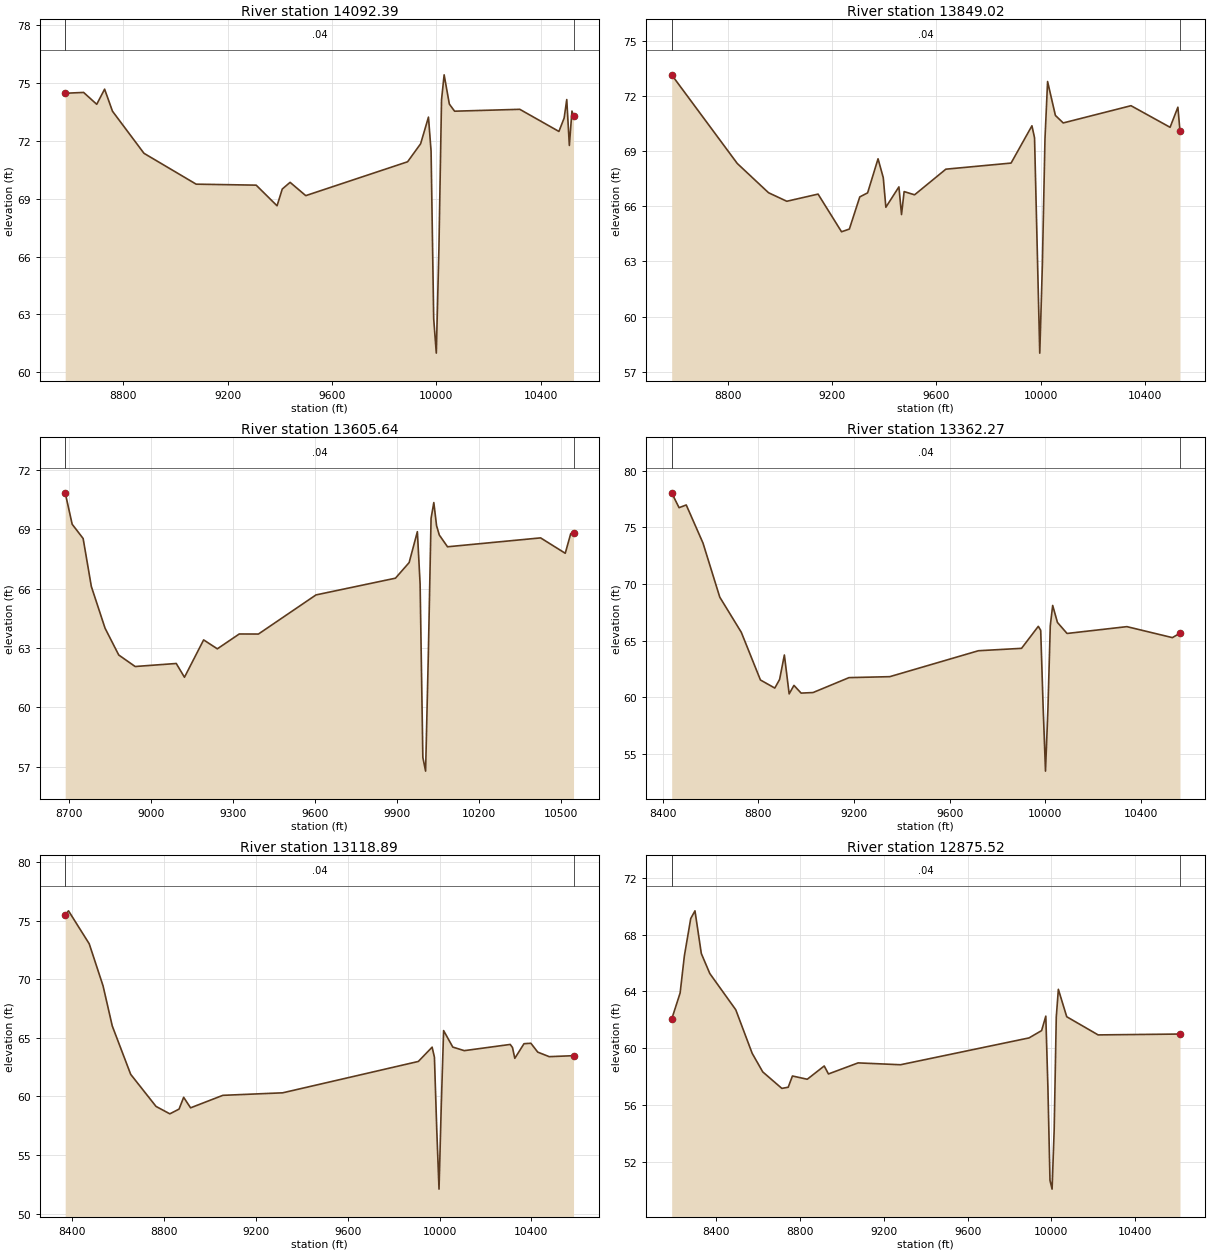
Type RM Length L Ch R = 1 ,14092.39,243.374800,243.374800,243.374800
XS GIS Cut Line= 6
445515.071856916729446.650106266445226.079429865729412.392719254
444679.198351949729432.471907318443998.547664911729467.372837007
443764.358184397729475.520843789443568.975148648729477.436268166
#Sta/Elev= 30
8576.74974.459318647.31174.501948697.661 73.88768727.87174.671098758.08273.52941
8878.85271.348739078.98669.750359309.14169.699439389.19568.630229409.20969.49878
9439.24569.845259499.32469.15656 9889.8470.909889939.90671.844469969.94673.22327
9979.95971.457269989.97262.779019999.98660.99836   1001066.4047110020.0174.11526
10030.0275.4141210050.0573.8981510070.0773.5302110320.2473.6274310470.2672.48138
10490.2673.1737710500.2674.1324910510.2671.7559210520.2673.5361410526.2873.27772
#Mann= 3 , 0 , 0
8576.749    0.04       08576.749    0.04       010526.28    0.04       0
#XS Ineff= 2 , 0
       09582.211                       0
Bank Sta=8576.749,10526.28
Exp/Cntr=0.3,0.1

Type RM Length L Ch R = 1 ,13849.02,243.374700,243.374700,243.374700
XS GIS Cut Line= 6
445496.681673199729173.424519241 445196.95117417729162.884554192
 444789.20994857729180.875566751444036.585388094 729221.87190941
443751.530911714729234.023533791443546.932120889729238.741766959
#Sta/Elev= 30
8583.78573.141498835.62268.322748955.72266.73129 9025.7966.267529145.90766.65688
9235.99464.608769266.02464.75673 9306.0766.504799336.11566.724329376.174 68.5766
9396.20467.551549406.21965.942799456.29367.050039466.30865.545829476.32366.79374
9516.38366.617929636.56268.011759886.93568.343929967.05470.370899977.06969.71751
9997.09958.0112410007.11 62.804110017.1369.6561110027.1472.7771110057.1870.93344
 10087.270.5260110347.4371.4629910497.4770.2893110527.4871.3811110535.5570.07891
#Mann= 3 , 0 , 0
8583.785    0.04       08583.785    0.04       010535.55    0.04       0
#XS Ineff= 2 , 0
       09514.264                       0
Bank Sta=8583.785,10535.55
Exp/Cntr=0.3,0.1

Type RM Length L Ch R = 1 ,13605.64,243.374800,243.374800,243.374800
XS GIS Cut Line= 6
445380.448416561 728907.63432233444846.508466095728932.629282981
444069.865161628728976.426773533443972.464324057728981.983280703
443705.397041172728993.674392089443524.740050882728998.433352202
#Sta/Elev= 30
8686.59870.844078712.07469.254948752.11868.534328782.15166.105648832.20663.99823
8882.26162.640798942.32662.05828 9092.4962.211489122.52361.51481  9192.6 63.4049
9242.66562.952819322.79263.703979392.90463.700779603.237 65.67979893.69866.52601
9943.77867.316949973.82568.878429983.84166.222779993.85757.4578110003.8756.76663
10013.8962.6791710023.9169.5523410033.9270.3513910043.9469.1837310053.9568.71023
   1008468.11499 10424.368.5647510514.3367.7863510534.3468.77906 10544.6 68.8107
#Mann= 3 , 0 , 0
8686.598    0.04       08686.598    0.04       0 10544.6    0.04       0
#XS Ineff= 2 , 0
       09441.512                       0
Bank Sta=8686.598,10544.6
Exp/Cntr=0.3,0.1

Type RM Length L Ch R = 1 ,13362.27,243.374800,243.374800,243.374800
XS GIS Cut Line= 6
445615.931892663728682.408931151444996.340019315728687.095827684
444210.074726194728728.100141048444056.274748683728733.492556721
443691.601612657728745.848220453 443493.22386238 728751.40614742
#Sta/Elev= 30
8438.16278.037468469.09576.727678499.09676.967838569.09873.60724  8639.168.84348
8729.10265.741258809.10561.536788869.10660.822818889.10761.579458909.108 63.7394
8929.10860.310028949.10961.06098 8979.1160.379089029.11160.430049179.27761.74466
9349.50861.82863 9720.0164.115229900.21464.327049970.25766.267279980.26365.91626
9990.26959.2509110000.2753.5006410010.2858.8814610020.2966.3223210030.2968.10876
 10050.366.6084310090.3365.6378410340.4766.2392110530.5565.2709510562.3465.66303
#Mann= 3 , 0 , 0
8438.162    0.04       08438.162    0.04       010562.34    0.04       0
#XS Ineff= 2 , 0
       09370.222                       0
Bank Sta=8438.162,10562.34
Exp/Cntr=0.3,0.1

Type RM Length L Ch R = 1 ,13118.89,243.374800,243.374800,243.374800
XS GIS Cut Line= 6
445669.350696087 728559.54568328444563.629650742728464.335361779
444056.701126069728490.224016219443816.707024068728500.858310848
443510.883141756728510.544360846443459.161842793728511.710453987
#Sta/Elev= 30
8368.68675.49307 8383.0975.829828473.42373.016288533.64569.430398573.79366.00932
8654.08961.884198764.49659.147938824.71858.514628864.866 58.9198 8884.9459.92486
8915.05159.027319055.56960.093019316.53160.308489907.687 62.98299967.76564.20368
9977.77863.34315 9987.7957.261949997.79652.09429 10007.859.3407710017.8165.61589
10057.8664.2088510107.91 63.904710308.0764.4345110318.07 64.172610328.08 63.2486
 10368.164.4962610398.1164.5354810428.1363.7778910478.1563.3920510584.0363.47534
#Mann= 3 , 0 , 0
8368.686    0.04       08368.686    0.04       010584.03    0.04       0
#XS Ineff= 2 , 0
       09303.548        10063.66       0
Bank Sta=8368.686,10584.03
Exp/Cntr=0.3,0.1

Type RM Length L Ch R = 1 ,12875.52,243.374800,243.374800,243.374800
XS GIS Cut Line= 6
 445834.94898665728452.708076462 444438.56285429 728232.49928309
444193.537757397728243.534129098444039.688751608728247.353085116
443883.826947033728250.703852758 443424.10962829728265.046722412
#Sta/Elev= 30
8186.18762.03104 8226.6363.887178246.87766.500418277.24869.128298297.49569.67244
8327.86666.66164 8368.3665.255018492.45262.698718570.83259.62847 8621.4558.31904
8712.56257.158738742.93357.23924 8763.1858.032298834.04557.802958915.03458.73831
8935.28158.176079077.01158.955899279.482 58.82519893.65660.715919953.67561.23206
9973.68162.249779983.68457.252839993.68750.6789710003.6950.0592110013.6954.22723
10023.6962.16996 10033.764.1393710073.71  62.20810223.7660.9275810614.8460.98873
#Mann= 3 , 0 , 0
8186.187    0.04       08186.187    0.04       010614.84    0.04       0
#XS Ineff= 2 , 0
       09250.143        10068.95       0
Bank Sta=8186.187,10614.84
Exp/Cntr=0.3,0.1

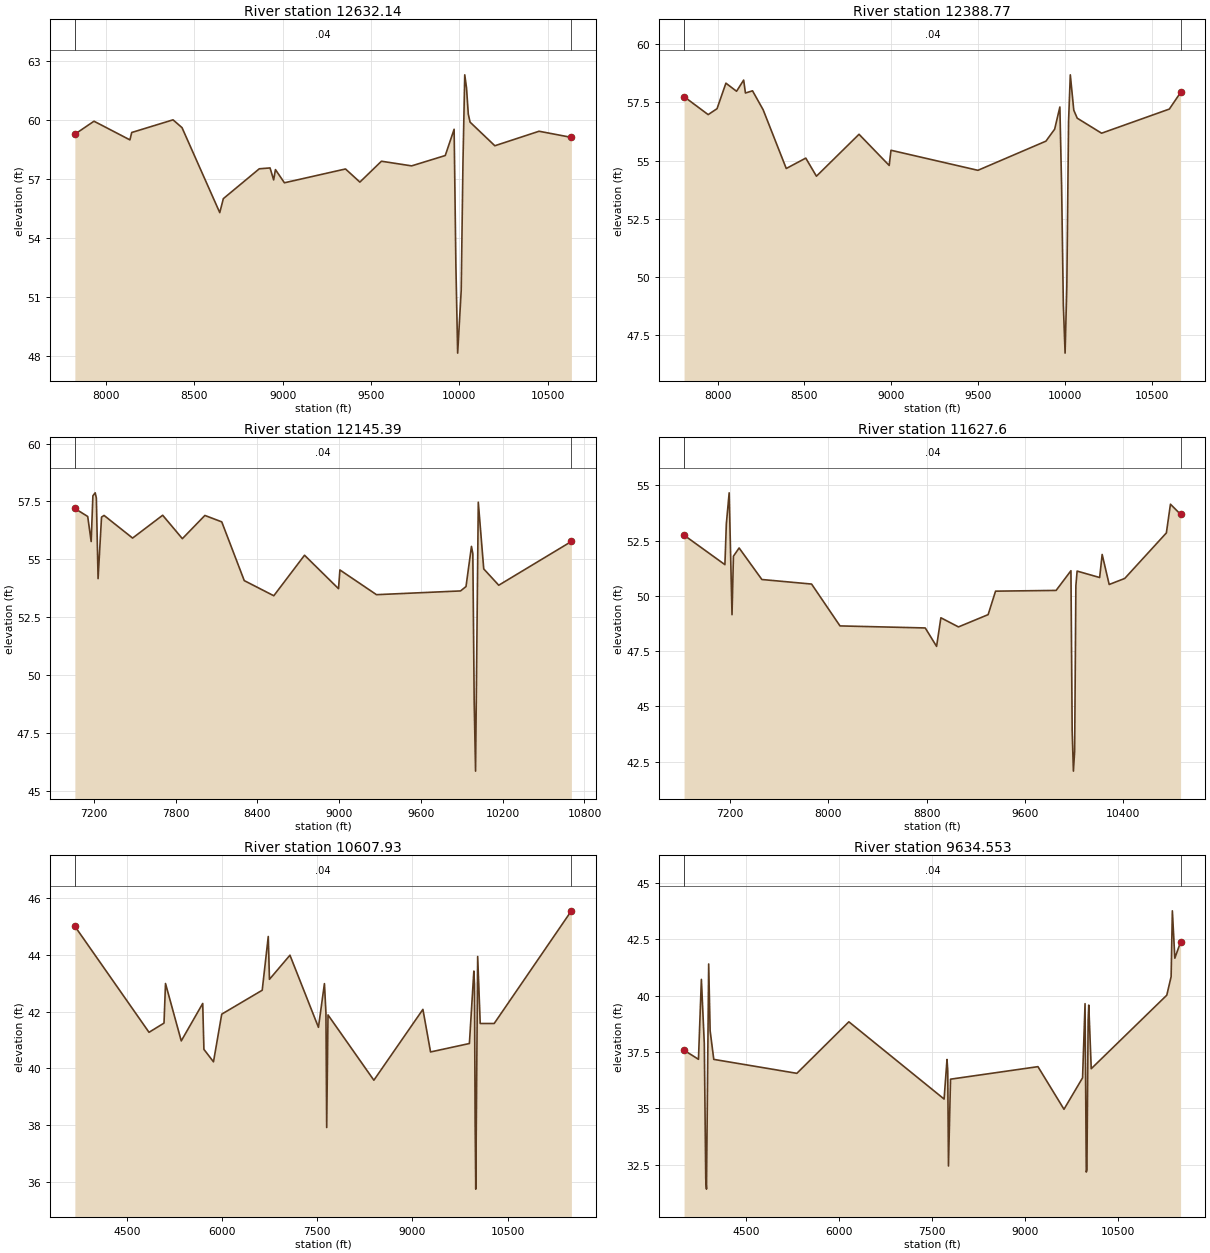
Type RM Length L Ch R = 1 ,12632.14,243.374800,243.374800,243.374800
XS GIS Cut Line= 6
446171.487448186728303.135426894444425.150145531 727975.74418731
444180.401353657727991.792268962443885.559082776728015.618057579
443662.970946074728028.198453888443391.959060222 728038.80198355
#Sta/Elev= 30
7823.06759.27599 7931.4159.935918134.89458.989158145.06859.363838379.07560.00637
8429.94659.609478643.60555.297898663.95356.006778867.43757.521358928.48357.56512
8948.83156.958248959.00557.480449009.87656.81136  9355.8 57.51269437.19356.84631
9559.28457.905449730.25857.669359920.75658.194879970.92359.527679980.95652.62337
 9990.9948.1662410011.0651.3502610021.0957.8738710031.1262.2906110041.1561.62884
10051.1860.2961410061.2159.8898810201.5658.69092 10451.959.4271410635.0759.11558
#Mann= 3 , 0 , 0
7823.067    0.04       07823.067    0.04       010635.07    0.04       0
#XS Ineff= 2 , 0
       09177.887        10065.71       0
Bank Sta=7823.067,10635.07
Exp/Cntr=0.3,0.1

Type RM Length L Ch R = 1 ,12388.77,243.374700,243.374700,243.374700
XS GIS Cut Line= 6
446160.803687513728089.460213199444467.427619129727726.212349966
444006.055189431727761.879398823443901.127760947727768.159631833
 443607.46592316727783.419704184443340.225576699727793.946725577
#Sta/Elev= 30
7806.35357.749397945.24656.976787996.38357.23196 8047.5258.330458108.88557.98224
8149.795 58.46328160.02357.906748200.93358.001378262.29857.181468395.25554.65642
8507.75755.103918569.12254.324328814.58256.129658988.44954.787398998.67755.44186
9499.82454.578069891.732 55.83449941.88156.349179971.97157.304499982.00153.89644
9992.03148.7721110002.0646.7062810012.0749.6000710022.0956.6823710032.1158.68988
10052.1557.1664110072.1856.8219310212.3956.17595 10602.857.2152910667.62 57.9304
#Mann= 3 , 0 , 0
7806.353    0.04       07806.353    0.04       010667.62    0.04       0
#XS Ineff= 2 , 0
       09099.736        10059.91       0
Bank Sta=7806.353,10667.62
Exp/Cntr=0.3,0.1

Type RM Length L Ch R = 1 ,12145.39,517.795200,517.795200,517.795200
XS GIS Cut Line= 6
446749.444200009728396.611485794446310.216053307728054.989593953
444182.835625142727510.348452598443996.803667486727518.668545857
443556.663944215727536.942642033443292.261507779 727545.68109335
#Sta/Elev= 30
7060.34957.197117154.65956.852677179.99655.771927192.66557.744217209.56757.87277
7218.00257.651777230.67154.171427256.00856.82649 7274.7256.897767484.04355.92147
7704.75456.90632 7849.2755.89596 8014.43  56.897  8138.356.62069 8303.4654.08662
8520.23353.433758745.70855.181418995.06953.738859005.392 54.54649273.77753.48035
9890.69653.641679930.73553.830859970.77555.562819980.78555.244869990.79548.86628
10000.8145.8704310020.8257.4676710060.8654.5913610170.9553.8875610704.0755.77455
#Mann= 3 , 0 , 0
7060.349    0.04       07060.349    0.04       010704.07    0.04       0
#XS Ineff= 2 , 0
       09047.273        10050.69       0
Bank Sta=7060.349,10704.07
Exp/Cntr=0.3,0.1

Type RM Length L Ch R = 1 , 11627.6,1019.673000,1019.673000,1019.673000
XS GIS Cut Line= 4
446852.473024517727935.693060279445029.197926044726868.062731773
443788.721137255727024.701348662443170.548190087727322.942682818
#Sta/Elev= 30
6822.70952.74121 7155.8451.408897167.42853.246917190.60554.656627213.78149.14569
 7225.3751.790827271.72352.162597457.36650.736247862.72350.530478094.48948.63769
8789.78448.545278882.25747.712098917.25549.005649060.75148.592419302.65649.14759
9363.13350.209619857.02450.242979977.97751.133719988.05643.890299998.13642.07003
10008.2242.9754610018.2950.4561410028.3751.1165810212.2350.8260810232.6151.86973
10289.9550.5109510416.7250.7843610756.28 52.843110789.5954.1423210872.25 53.6838
#Mann= 3 , 0 , 0
6822.709    0.04       06822.709    0.04       010872.25    0.04       0
#XS Ineff= 2 , 0
       08753.345        10046.58       0
Bank Sta=6822.709,10872.25
Exp/Cntr=0.3,0.1

Type RM Length L Ch R = 1 ,10607.93,973.373200,973.373200,973.373200
XS GIS Cut Line= 6
449624.134324133728237.791509107446260.419046372 726121.90609245
444291.145567864725952.708076462443719.137546062725992.457608208
442818.953881681726024.608906731442418.936124295726031.270488217
#Sta/Elev= 30
3681.91944.995274850.47241.26976 5086.7541.592935110.378 42.98425358.67640.96722
5696.73642.283365715.51740.670725866.46740.23293 5996.4241.90765 6634.37  42.748
6729.69444.636496748.47543.130567071.484 43.97857520.41341.444657614.92442.97995
7638.552 41.95337650.36537.925597671.25341.879978393.90639.586379166.74342.07498
9287.18540.578999899.35540.875889969.59343.420839979.62742.94515 9989.6638.09814
9999.69335.7599510029.7343.9319710069.7741.5792410289.9941.5788411506.6245.53769
#Mann= 3 , 0 , 0
3681.919    0.04       03681.919    0.04       011506.62    0.04       0
#XS Ineff= 2 , 0
       0 8439.75        10039.44       0
Bank Sta=3681.919,11506.62
Exp/Cntr=0.3,0.1

Type RM Length L Ch R = 1 ,9634.553,1216.716500,1216.716500,1216.716500
XS GIS Cut Line= 6
449732.641268581727391.437342435446086.807935208725123.642203569
444136.231038064 725007.19525595443879.967112064725010.548507333
443120.109770626725040.308645919442362.005354196725052.368994385
#Sta/Elev= 30
3495.06537.572913727.82237.171483774.92940.717093822.03637.868753845.58931.86618
3857.36631.411973892.69641.39804 3916.2538.438713975.13337.16758 5317.6836.54881
6157.86238.83479 7696.58 35.40847743.68737.164567755.46336.65746 7767.2432.44073
7800.49336.289239213.00436.844759633.75234.955349933.96236.349479973.965 39.6378
9993.96732.1687910003.9732.2631110023.9938.89814   10034 39.576110074.04 36.7538
11294.6740.0152111364.67 40.835611384.6743.7576511424.6741.6561111517.6742.37231
#Mann= 3 , 0 , 0
3495.065    0.04       03495.065    0.04       011517.67    0.04       0
#XS Ineff= 2 , 0
       08064.401                       0
Bank Sta=3495.065,11517.67
Exp/Cntr=0.3,0.1

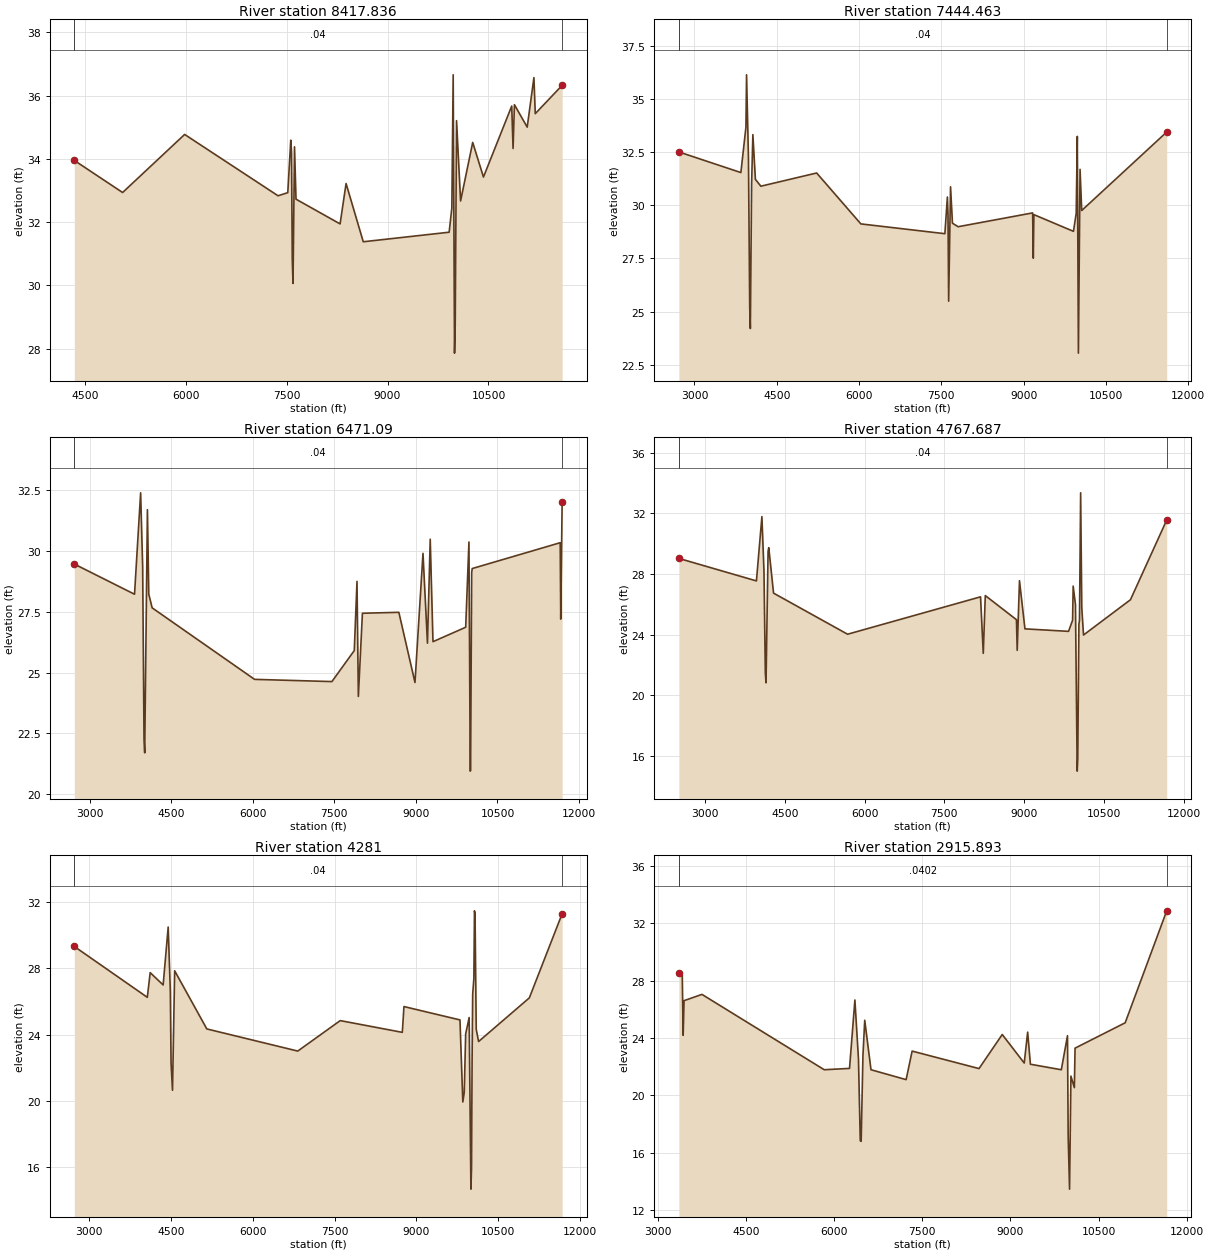
Type RM Length L Ch R = 1 ,8417.836,973.373200,973.373200,973.373200
XS GIS Cut Line= 6
448951.391268551 726121.90609245444125.120311171723785.891315281
443471.371529818723805.773074508443084.120514631723813.872379422
442666.335366488723815.268366203442235.635183841723806.482815862
#Sta/Elev= 30
4343.47833.952825061.60532.938515983.719 34.77417372.44332.835017516.87132.93421
 7561.3134.59313 7572.4234.221277583.52930.834797594.63930.065687616.85934.38252
7639.07832.728228294.55731.945938383.43533.22337 8638.9631.381589915.58531.68333
9955.60332.445279975.61236.658779995.62227.8612710005.6328.7338210025.6435.20992
10085.6632.6711610265.7534.52191 10425.833.4272910845.88 35.672310865.8834.33052
10885.8835.7146111075.8835.0050611175.8836.5719711195.8935.4310911595.3536.32668
#Mann= 3 , 0 , 0
4343.478    0.04       04343.478    0.04       011595.35    0.04       0
#XS Ineff= 2 , 0
       07661.067        10039.06       0
Bank Sta=4343.478,11595.35
Exp/Cntr=0.3,0.1

Type RM Length L Ch R = 1 ,7444.463,973.373200,973.373200,973.373200
XS GIS Cut Line= 6
450166.669046342726284.666509107444076.169384778722814.717567772
443447.178245306722830.338152036443074.600175023722832.346518368
 442680.06162712722822.445056498442197.015828252722790.885873154
#Sta/Elev= 30
2716.74132.508683846.55431.538753938.62733.674683950.13636.136463984.66332.25338
4007.68125.17133 4019.1924.203524042.20931.015584065.22733.324424111.26331.21855
4210.93630.897025227.64631.518556033.28329.123467563.99328.66288 7610.03 30.3887
7621.53929.526067633.04825.490397667.57530.868557702.10229.157037805.68428.99098
9163.75829.641129175.26727.513059186.77629.55994 9907.5928.773599957.607 29.6238
9977.61433.239029997.62123.0448510027.6331.6872310057.6429.7534611606.9233.44515
#Mann= 3 , 0 , 0
2716.741    0.04       02716.741    0.04       011606.92    0.04       0
#XS Ineff= 2 , 0
       07284.179        10042.41       0
Bank Sta=2716.741,11606.92
Exp/Cntr=0.3,0.1

Type RM Length L Ch R = 1 , 6471.09,1703.403100,1703.403100,1703.403100
XS GIS Cut Line= 6
449862.946313173725579.233283266445240.270246655722129.832184121
444794.812184989721950.472767517444413.127518624721861.117720291
443090.153092891721844.417931482442089.314881593721725.000000015
#Sta/Elev= 30
2715.365 29.46533823.27328.222233935.56732.396553972.99929.357513997.95322.25269
 4010.4321.695114060.33931.701884085.293 28.22454147.67927.662096031.73424.71889
7454.13424.627567865.88125.905147915.78928.749227940.74424.017548015.60727.43975
8685.72827.478758982.53324.590459129.92429.905549212.05526.20914 9263.01  30.486
9313.77726.270419915.31526.863429975.359 30.3717    999920.9421510005.38 20.9677
 10025.429.11185 10035.429.2798911654.0230.3432111664.0327.2000811689.7532.02569
#Mann= 3 , 0 , 0
2715.365    0.04       02715.365    0.04       011689.75    0.04       0
#XS Ineff= 2 , 0
       06921.745                       0
Bank Sta=2715.365,11689.75
Exp/Cntr=0.3,0.1

Type RM Length L Ch R = 1 ,4767.687,486.686600,486.686600,486.686600
XS GIS Cut Line= 6
450036.557424277725590.083977684445120.220632851721575.563015565
 444880.41107893721306.045922741444718.161394417721060.113989964
444237.877462029 720012.90981847443695.749206126719164.776618004
#Sta/Elev= 30
2512.26329.032213969.02327.549164072.01531.786234110.63728.212224136.38521.47267
4149.25920.83572 4187.8829.486324200.75429.740164290.87226.744135681.25824.03667
8178.80226.500828230.29822.776318268.25426.583158853.49524.995338867.61222.97571
8910.57127.56403 9013.0724.390629832.52124.226169908.10924.959479918.90727.20908
  9962.125.988589994.49415.0161210005.2915.8459710026.8724.7021610037.6624.96139
10059.25 33.354110080.8325.7776610113.21 23.984910995.2126.3098311676.1731.56122
#Mann= 3 , 0 , 0
2512.263    0.04       02512.263    0.04       011676.17    0.04       0
#XS Ineff= 2 , 0
       06967.749                       0
Bank Sta=2512.263,11676.17
Exp/Cntr=0.3,0.1

Type RM Length L Ch R = 1 ,    4281,1365.107300,1365.107300,1365.107300
XS GIS Cut Line= 6
450069.109507591 725514.12911658445709.406236589721750.555951029
445476.065389961721454.689598009445286.610126823721147.607745856
444642.526701838719677.166700155444244.365547568718927.367418587
#Sta/Elev= 30
2723.67429.329824063.38326.259954116.226 27.74894354.018 27.00634446.49330.50219
4486.12526.595844499.33622.282564525.757 20.64914565.38927.86122 5155.5524.35154
6824.418 23.01467603.84924.854088743.13924.145188773.15125.701729801.21924.89506
9853.43919.941549879.54820.509939905.658 24.0466 9969.5825.0401810002.0614.68163
10012.8815.9200310023.7122.5318810034.54 26.4412 10056.227.4070910067.0231.48044
10077.8531.2913610099.5124.3299910142.8223.5906411074.2926.22611 11676.231.30469
#Mann= 3 , 0 , 0
2723.674    0.04       02723.674    0.04       0 11676.2    0.04       0
#XS Ineff= 2 , 0
       07248.669                       0
Bank Sta=2723.674,11676.2
Exp/Cntr=0.3,0.1

Type RM Length L Ch R = 1 ,2915.893,0.000000,0.000000,0.000000
XS GIS Cut Line= 3
450372.928952038725188.608283252447193.675479829721542.774949923
445403.310896516718580.535366595
#Sta/Elev= 30
3360.62928.558383418.33928.387633433.55424.18965 3448.7726.606493753.07627.04392
5833.28421.78278  6263.621.875746354.89226.652086415.75322.533156446.18416.82694
6461.399 16.78316491.82922.77665 6522.26 25.23676628.76721.782287226.43421.09122
7328.67123.084138466.05521.862948861.379 24.24249235.28622.249669293.70924.40858
9340.44722.167239866.25321.781249971.41424.159359983.09917.1176210006.4713.44472
10029.8421.3365510088.2620.5320310099.9423.2890710952.9225.0616911659.2132.88006
#Mann= 3 , 0 , 0
3360.629  0.0402       03360.629  0.0402       011659.21  0.0402       0
#XS Ineff= 2 , 0
       08106.436                       0
Bank Sta=3360.629,11659.21
Exp/Cntr=0.3,0.1